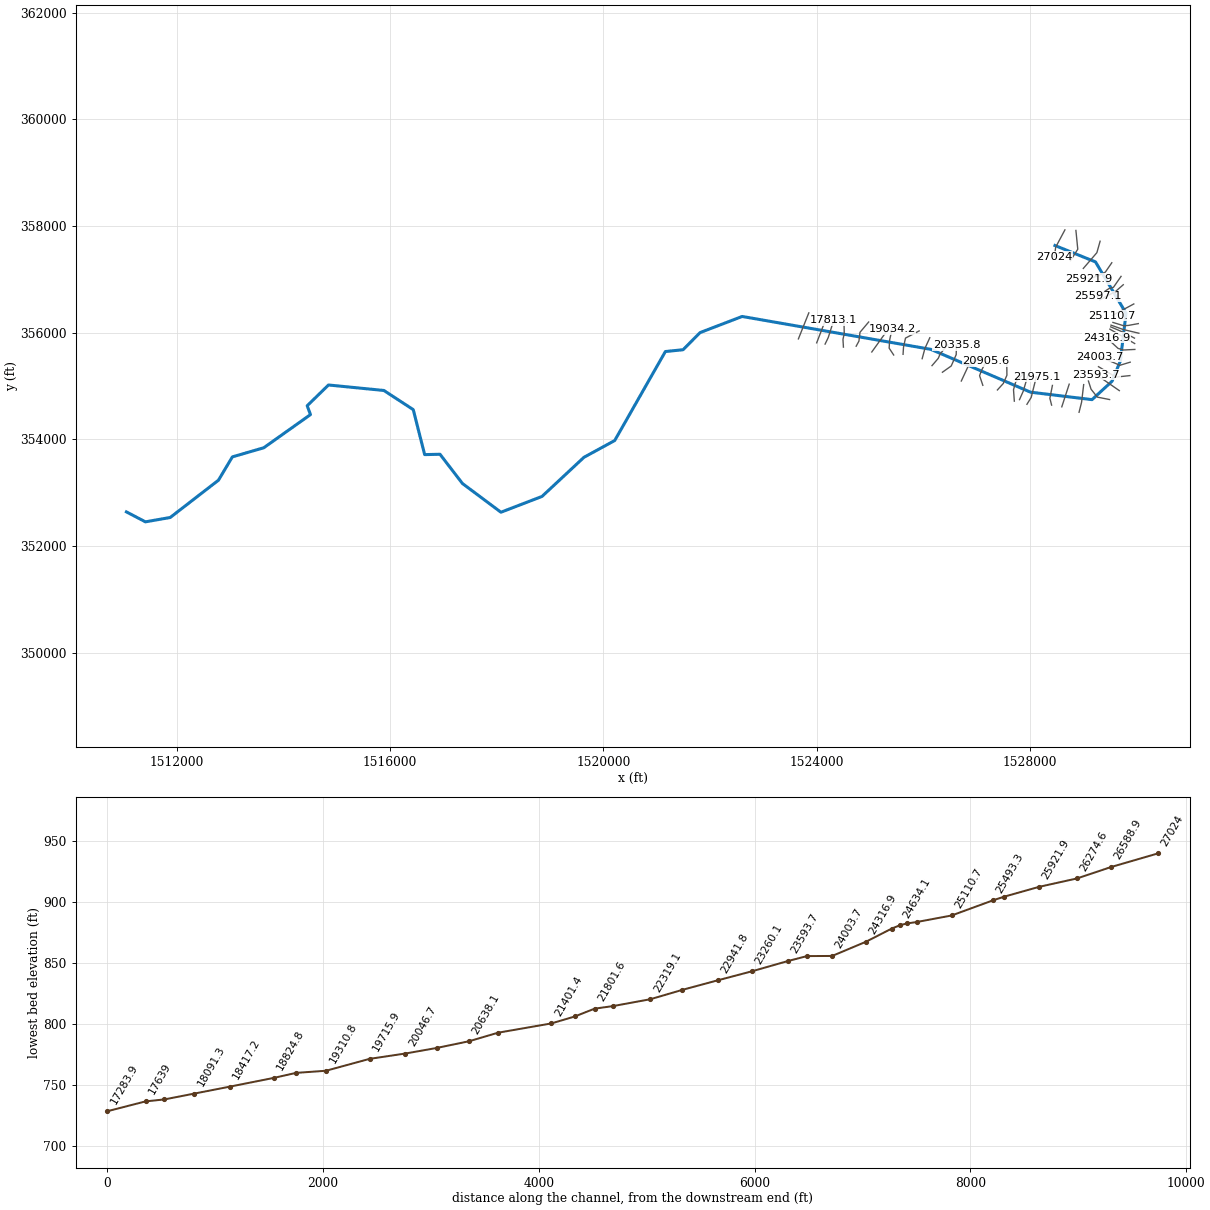
--- BENSRN.prj (project) ---

Proj Title=BENSRN
Current Plan=p01
Default Exp/Contr=0,0
English Units
Geom File=g01
Geom File=g02
Flow File=f01
Plan File=p01
BEGIN DESCRIPTION:
END DESCRIPTION:
DSS Export Rating Curves= 0
DSS Export Rating Curve Sorted= 0
DSS Export Volume Flow Curves= 0
DXF Filename=..\..\..\..\04_EngrWorking\AFG\Approximate\BENSRN\BENSRN.
DXF OffsetX= 0
DXF OffsetY= 0
DXF ScaleX= 0
DXF ScaleY= 0

--- BENSRN.p01 (plan) ---

Plan Title=Floodplain
Program Version=4.00
Geom File=g01
Flow File=f01
K Sum by GR=0
Std Step Tol=0.01
Critical Tol=0.01
Num of Std Step Trials=20
Max Error Tol=0.3
Flow Tol Ratio=0.001
Split Flow NTrial=30
Split Flow Tol=0.02
Split Flow Ratio=0.02
Log Output Level=0
Friction Slope Method=1
Unsteady Friction Slope Method=2
Unsteady Bridges Friction Slope Method=1
Global Log Level=0
CheckData=False
Run HTab=0
Run UNet=0
Run PostProcess=0
UNET Theta=0
UNET Theta Warmup=0
UNET ZTol=0
UNET ZSATol=0
UNET MxIter=0
UNET MaxInSteps=0
UNET DtIC=0
UNET DtMin=0
UNET MaxCRTS=0
UNET WFStab=0
UNET SFStab=0
UNET WFX=0
UNET SFX=0
UNET DSS MLevel=0
UNET DZMax Abort=0
UNET Convert EG Bridges=0
UNET Use Existing IB Tables=0
UNET Froude Limit=0
UNET Froude Power=0
Write IC File=0
Echo Input=False
Echo Output=False
Write Detailed=0

--- BENSRN.f01 (steady flow) ---

Flow Title=NFF Regression Equation
Program Version=4.10
Number of Profiles= 1
Profile Names=P100yr
River Rch & RM=BENSRN,Main            ,27024
118.1317
River Rch & RM=BENSRN,Main            ,24786
144.1826
River Rch & RM=BENSRN,Main            ,24003.7
154.3408
River Rch & RM=BENSRN,Main            ,23260.1
177.9647
River Rch & RM=BENSRN,Main            ,22941.8
202.1304
River Rch & RM=BENSRN,Main            ,22319.1
216.7371
River Rch & RM=BENSRN,Main            ,21975.1
256.2404
River Rch & RM=BENSRN,Main            ,21401.4
269.0166
River Rch & RM=BENSRN,Main            ,20638.1
296.8621
River Rch & RM=BENSRN,Main            ,20046.7
361.6444
River Rch & RM=BENSRN,Main            ,19310.8
392.8883
River Rch & RM=BENSRN,Main            ,18417.2
 435.534
River Rch & RM=BENSRN,Main            ,18091.3
521.3551
River Rch & RM=BENSRN,Main            ,16354.7
566.4985
River Rch & RM=BENSRN,Main            ,16071.4
806.4322
River Rch & RM=BENSRN,Main            ,14642.8
855.1403
River Rch & RM=BENSRN,Main            ,13603.3
915.6908
River Rch & RM=BENSRN,Main            ,12320
996.9082
River Rch & RM=BENSRN,Main            ,9939.8
1167.976
River Rch & RM=BENSRN,Main            ,6910.5
1285.777
River Rch & RM=BENSRN,Main            ,2097.5
1393.506
Boundary for River Rch & Prof#=BENSRN,Main            , 1
Up Type= 0
Dn Type= 3
Dn Slope=0.003
DSS Import GetInterval= 0
DSS Import GetPeak= 0
DSS Import FillOption= 0

--- BENSRN.g01 (geometry) ---

Geom Title=USGS 10m DEM
Program Version=4.10

River Reach=BENSRN          ,Main
Reach XY= 30
     1528465.411      357632.167     1529225.298       357324.68
     1529797.347      356362.874     1529691.444      355466.173
     1529534.943      355086.716     1529160.453      354741.931
     1528006.722      354882.145      1526139.36      355684.923
     1522602.555       356301.59     1521815.185      355999.984
     1521494.005      355677.718     1521163.058      355644.081
     1520213.623      353975.244     1519638.536      353661.659
     1518850.775      352927.067     1518081.461      352630.843
     1517359.429       353169.58     1516938.856      353717.757
     1516651.096      353711.247     1516437.554      354554.563
     1515887.207      354913.938     1514848.717      355016.697
      1514449.49      354627.479     1514511.339      354461.464
     1513635.688      353839.719     1513046.495      353668.278
     1512787.163       353232.08     1511882.215       352532.21
     1511417.328      352450.827     1511061.155      352637.306

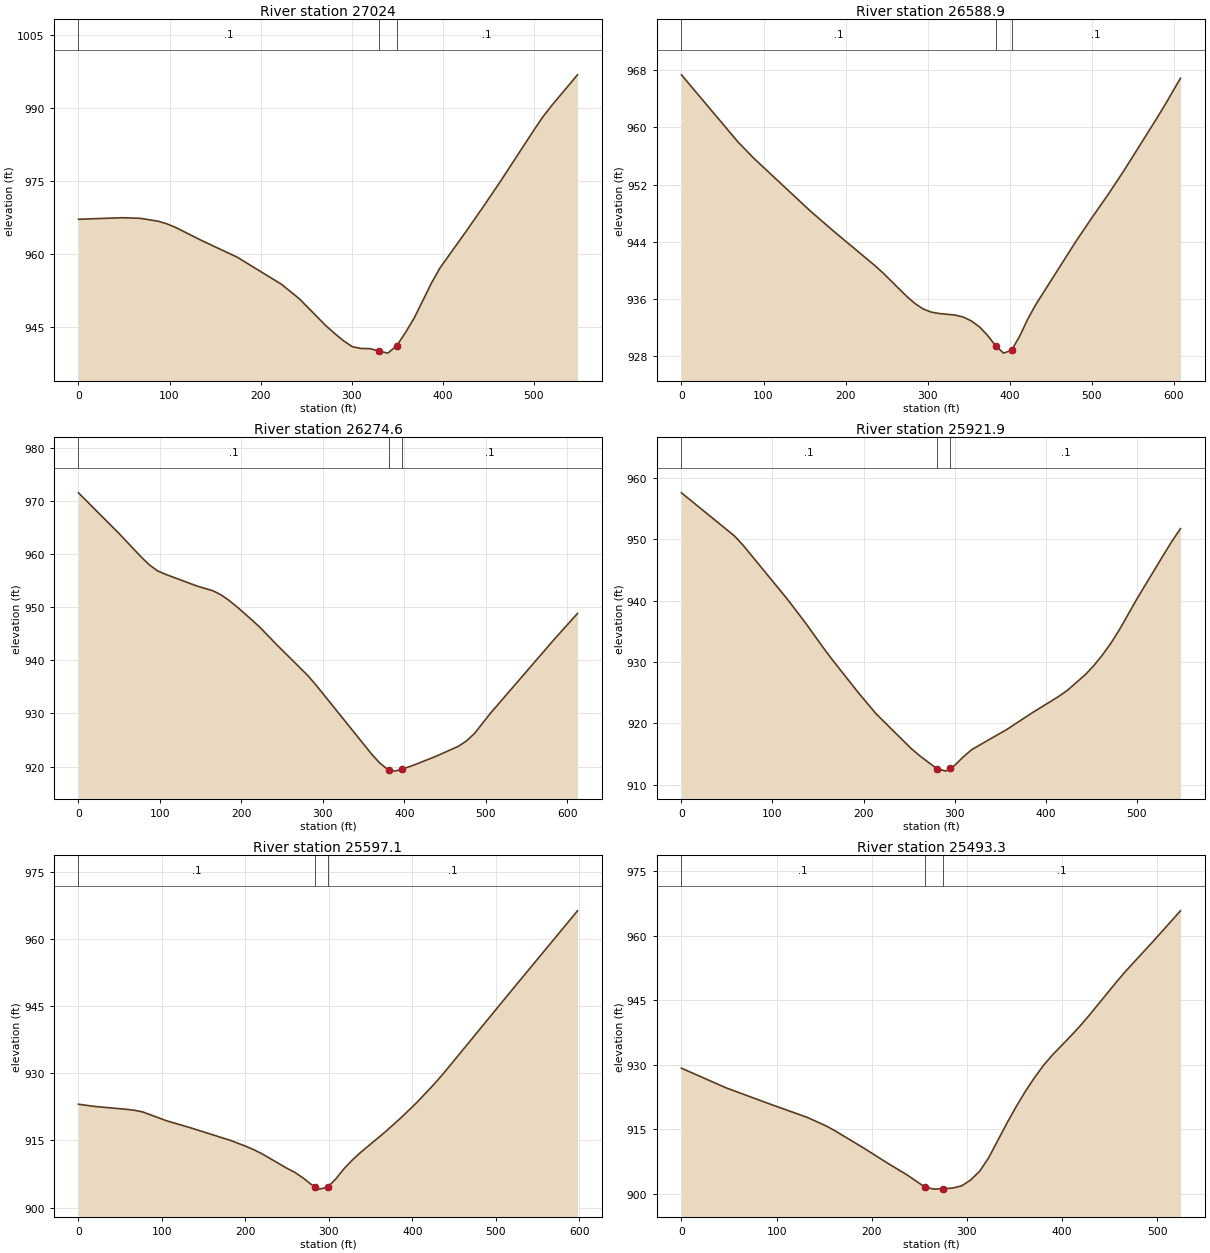
Type RM Length L Ch R = 1 ,27024   ,435.7,435.2,432.3
XS GIS Cut Line= 3
     1528651.927       357925.19     1528478.316      357599.669
     1528456.615      357421.718
#Sta/Elev= 30
       0  967.15    48.5  967.47      68  967.34    87.4  966.75    97.1  966.21
   106.8  965.46   135.9  962.72   174.8   959.3   223.3  953.72   242.7  950.76
   271.8  945.22   281.6   943.6   291.3   942.1     301  940.89   310.7  940.54
   320.4   940.5   330.1939.9957   339.8  939.58   349.5  941.08   359.2  943.81
   368.9  946.84   387.8  954.02   397.2  957.14   425.5  964.57   444.4  969.66
   463.3  974.89     501  985.71   510.4   988.3   519.9  990.58   548.2   996.9
#Mann= 3 , 0 , 0
       0      .1       0   330.1    .045       0   349.5      .1       0
Bank Sta=330.1,349.5
XS Rating Curve= 0 ,0
Exp/Cntr=0.3,0.1

Type RM Length L Ch R = 1 ,26588.9 ,317.4,314.3,310.6
XS GIS Cut Line= 3
     1528858.091      357914.339     1528892.813      357562.777
     1528756.094      357347.933
#Sta/Elev= 30
       0  967.36    68.7  957.99    88.3  955.67     157  948.31   186.4  945.39
   235.5  940.69   245.3  939.68   274.8  936.33   284.6  935.36   294.4  934.61
   304.2  934.17     314  933.97   333.6  933.75   343.5  933.47   353.3  932.92
   363.1   932.1   372.9  930.91   382.7  929.47   392.4  928.43   402.2  928.84
     412  930.79   421.8  933.17   431.6  935.21   480.6  944.07   500.2   947.4
   519.8  950.62   539.4  954.02   578.6  961.19   588.3  963.02   607.9  966.88
#Mann= 3 , 0 , 0
       0      .1       0   382.7    .045       0   402.2      .1       0
Bank Sta=382.7,402.2
XS Rating Curve= 0 ,0
Exp/Cntr=0.3,0.1

Type RM Length L Ch R = 1 ,26274.6 ,361.3,352.7,343.7
XS GIS Cut Line= 3
      1529311.65      357712.516     1529250.886      357497.673
     1528996.979      357202.534
#Sta/Elev= 30
       0  971.51    48.5  964.06    77.7  959.32    87.4   957.9    97.1  956.82
   106.8  956.18   145.6  953.96     165  953.08   174.7  952.33   184.4  951.31
   194.2   950.1   213.6  947.49   223.3  946.11   242.7  943.03   281.7  937.09
   291.4  935.37   359.5  922.41   369.3  920.73     379  919.52   381.7  919.41
   388.7  919.13   396.7   919.5   408.2  920.07   437.4  921.82   466.6  923.82
   476.3  924.82   486.1   926.2   505.5  929.98   583.4  943.82   612.6  948.81
#Mann= 3 , 0 , 0
       0      .1       0   381.7    .045       0   396.7      .1       0
Bank Sta=381.7,396.7
XS Rating Curve= 0 ,0
Exp/Cntr=0.3,0.1

Type RM Length L Ch R = 1 ,25921.9 ,329.2,324.8,319.8
XS GIS Cut Line= 4
     1529530.834       357308.87     1529409.306      357133.089
     1529272.587      357063.645     1529101.146      357005.051
#Sta/Elev= 30
       0  957.54    58.3  950.51      68  948.96   116.6  940.18     136  936.41
   155.4   932.4   165.1  930.48   194.3     925   213.7  921.58     252  915.95
   261.6  914.74   280.5  912.62   290.4  912.22   295.5   912.7     300  913.13
   309.5  914.53   319.1  915.74   357.5  919.01   386.1  921.79   414.7  924.41
   424.3  925.42   443.3  927.88   452.9  929.38   462.4  931.12   471.9  933.07
   481.5  935.34   500.5   940.3   529.2  947.34   538.7  949.62   548.2  951.71
#Mann= 3 , 0 , 0
       0      .1       0   280.5    .045       0   295.5      .1       0
Bank Sta=280.5,295.5
XS Rating Curve= 0 ,0
Exp/Cntr=0.3,0.1

Type RM Length L Ch R = 1 ,25597.1 ,98.4,103.8,108.2
XS GIS Cut Line= 4
     1529704.343      357053.608     1529561.982      356848.747
     1529476.913      356824.441     1529261.635      356678.608
#Sta/Elev= 30
       0  923.09    19.2   922.6    57.6  921.95    67.2  921.73    76.8  921.38
   105.5   919.4   134.3  917.83   182.3  915.01   201.5  913.64   211.1  912.86
   220.7  911.95   249.5  908.83   259.3  907.88   269.1  906.66     279  905.18
   283.6   904.7   288.8  904.15   298.6  904.58   308.4  906.43   318.3  908.73
   328.1  910.63   337.9  912.31   366.8  916.79   386.1     920   405.4  923.46
   424.6  927.25   434.2  929.26   443.9  931.42   520.9  948.89     598  966.23
#Mann= 3 , 0 , 0
       0      .1       0   283.6    .045       0   298.6      .1       0
Bank Sta=283.6,298.6
XS Rating Curve= 0 ,0
Exp/Cntr=0.3,0.1

Type RM Length L Ch R = 1 ,25493.3 ,382.6,382.6,382.5
XS GIS Cut Line= 3
     1529745.677      356896.544     1529595.938      356766.336
     1529307.309      356614.426
#Sta/Elev= 30
       0  929.23    47.2  924.64    94.5  920.78   132.3   917.8   151.2  915.92
   160.6   914.8     189  911.04   217.6  907.05   236.8   904.5     256  901.61
   265.6  901.14   275.2  901.25   284.8  901.38   294.4  901.87     304  903.26
   313.6  905.32   323.1  908.48   342.3  916.52   351.9  920.31   361.5  923.83
   371.1  927.01   380.7  929.92   390.3  932.37   409.5  936.75   419.1  939.05
   428.7  941.52   457.4  949.28     467  951.76   495.8  958.67   524.6  965.78
#Mann= 3 , 0 , 0
       0      .1       0     256    .045       0   275.2      .1       0
Bank Sta=256,275.2
XS Rating Curve= 0 ,0
Exp/Cntr=0.3,0.1

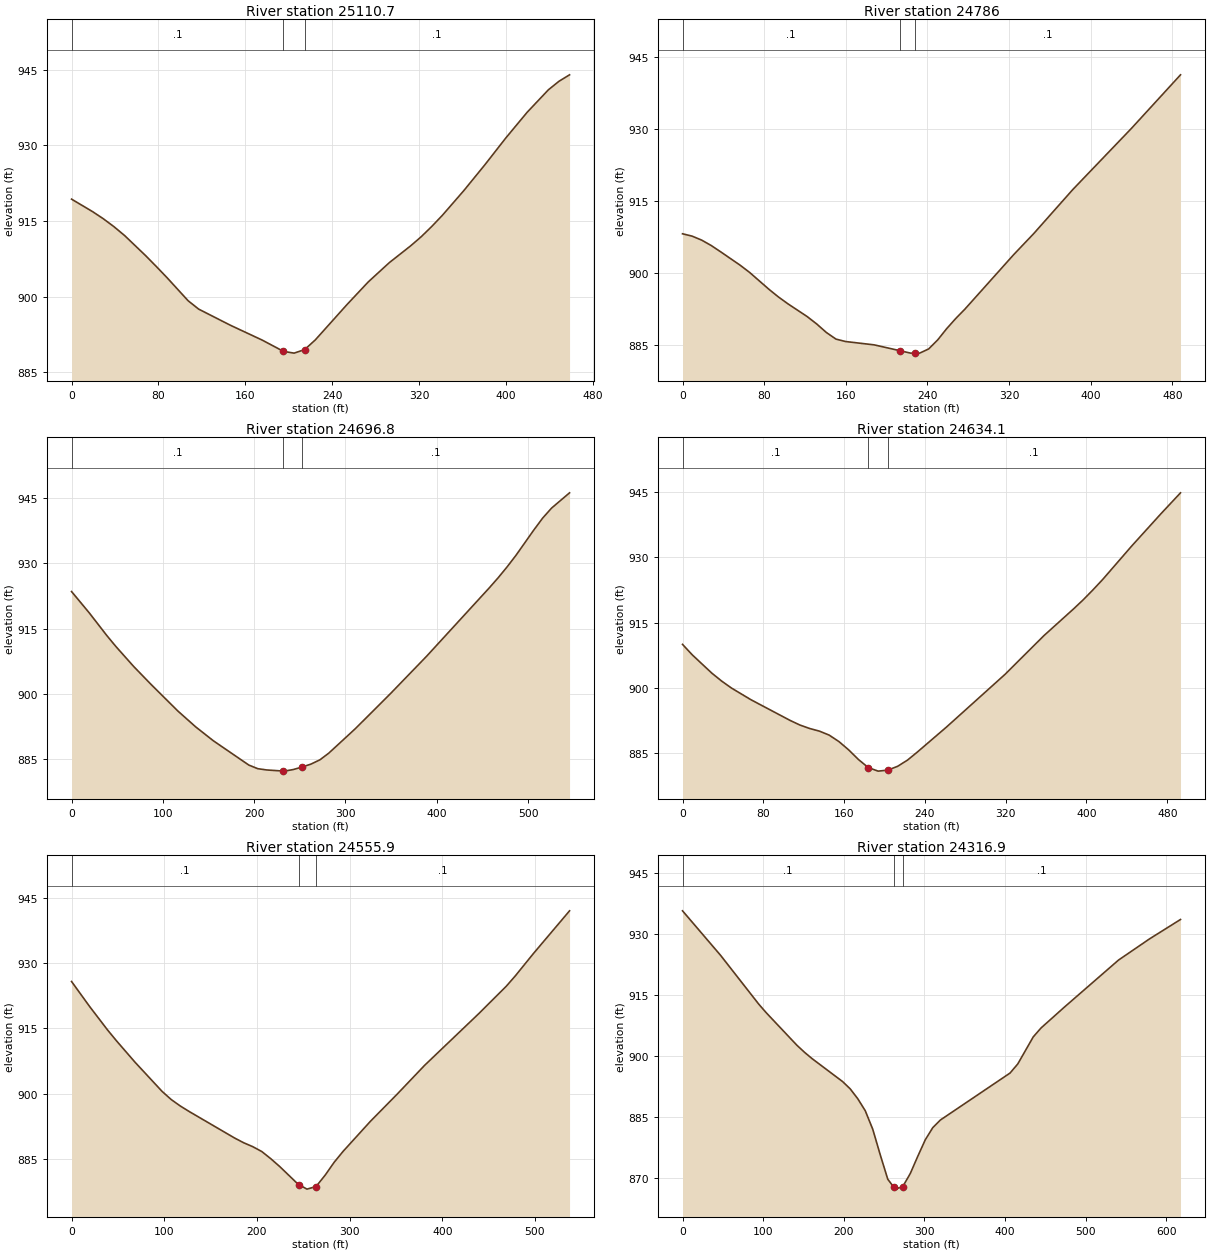
Type RM Length L Ch R = 1 ,25110.7 ,333.9,324.7,314.8
XS GIS Cut Line= 2
      1529943.16      356536.301     1529539.514      356319.287
#Sta/Elev= 30
       0  919.34    19.5  916.84    29.2  915.45      39  913.88    48.8  912.12
    68.3   908.1      78  905.97    87.8  903.77   107.3  899.17     117  897.51
   146.3   894.3   175.5  891.36     195  889.13   204.8  888.78   214.5  889.48
   224.3   891.4   253.5  898.42     273   902.9   292.5  906.75     312  910.06
   321.8  911.88   331.5  913.92   341.3  916.14   360.8  920.98   380.3  926.14
   399.8  931.52   419.3  936.58   438.8  941.03   448.5  942.72   458.3  944.01
#Mann= 3 , 0 , 0
       0      .1       0     195    .045       0   214.5      .1       0
Bank Sta=195,214.5
XS Rating Curve= 0 ,0
Exp/Cntr=0.3,0.1

Type RM Length L Ch R = 1 ,24786   ,95.9,89.2,82
XS GIS Cut Line= 4
      1530027.26      356167.757     1529842.364      356133.903
     1529753.823      356127.393        1529552.      356189.893
#Sta/Elev= 30
       0  908.21     9.4  907.72    18.8  906.89    28.2  905.76    37.6  904.43
    56.4  901.69    65.8  900.17    84.6  896.69      94  895.08   103.4  893.64
   122.2     891   131.6  889.45     141  887.69   150.4  886.32   159.8  885.82
     188  885.12   212.7  883.93   223.5  883.41   227.7  883.41   232.4  883.41
   241.2  884.28   250.1  886.17     259  888.53   267.9  890.64   276.8  892.57
   324.8  903.94     344  908.21   382.4  917.39     440  930.13     488  941.24
#Mann= 3 , 0 , 0
       0      .1       0   212.7    .045       0   227.7      .1       0
Bank Sta=212.7,227.7
XS Rating Curve= 0 ,0
Exp/Cntr=0.3,0.1

Type RM Length L Ch R = 1 ,24696.8 ,68.9,62.7,57
XS GIS Cut Line= 3
     1530038.646      355987.256     1529745.677        356056.7
     1529515.643      356139.166
#Sta/Elev= 30
       0  923.52    19.4  918.62    38.8  913.37    48.6  910.89      68  906.32
    87.4  902.12   116.6  896.05     136  892.43   155.4  889.23   194.2  883.66
     204  882.83   213.7  882.54   232.1  882.28   233.1  882.27   242.8  882.63
   252.5  883.21   262.2  883.88     272  884.86   281.7  886.39   310.9  892.03
     350  900.22   389.1   908.7   457.5  924.35   467.3  926.69     477  929.16
   486.8  931.84   506.4  937.67   516.1  940.41   525.9  942.71   545.5   946.2
#Mann= 3 , 0 , 0
       0      .1       0   232.1    .045       0   252.5      .1       0
Bank Sta=232.1,252.5
XS Rating Curve= 0 ,0
Exp/Cntr=0.3,0.1

Type RM Length L Ch R = 1 ,24634.1 ,79.1,78.2,77.2
XS GIS Cut Line= 3
     1529955.646      355895.622     1529749.916      356003.695
     1529510.333      356106.559
#Sta/Elev= 30
       0     910     9.7  907.58      29  903.39    38.7  901.57    48.4  899.97
    67.8  897.27   106.5  892.52   116.2  891.46   125.9  890.66   135.6  890.05
   145.2  889.14   154.9  887.65   164.6  885.73   174.3  883.51     184  881.67
   193.7  880.86   203.3  881.09     213  881.97   222.7  883.38   232.4  885.22
   261.4     891   319.3   903.1   357.9  912.02   386.9  918.09   396.6  920.21
   406.2  922.48   415.9  924.88   444.8  932.62   473.8  940.05   493.1  944.84
#Mann= 3 , 0 , 0
       0      .1       0     184    .045       0   203.3      .1       0
Bank Sta=184,203.3
XS Rating Curve= 0 ,0
Exp/Cntr=0.3,0.1

Type RM Length L Ch R = 1 ,24555.9 ,234.2,239,243.9
XS GIS Cut Line= 2
     1529959.552      355794.059     1529494.708      356063.591
#Sta/Elev= 30
       0  925.73    19.5  919.99    39.1  914.54    48.8  912.04    68.4  907.23
    97.7  900.51   107.5  898.65   117.2  897.18     127  895.89   175.8  889.83
   185.6  888.74   195.4  887.84   205.2  886.72   214.9  885.08   224.7  883.25
   244.2  879.26   245.3  879.13     254  878.09   263.8  878.69   273.6  881.29
   283.3  884.24   293.1  886.79   322.4  893.64   351.7  899.97     381  906.51
   439.6  918.41     469  924.64   478.7     927   498.2  932.12   537.3  941.95
#Mann= 3 , 0 , 0
       0      .1       0   245.3    .045       0   263.8      .1       0
Bank Sta=245.3,263.8
XS Rating Curve= 0 ,0
Exp/Cntr=0.3,0.1

Type RM Length L Ch R = 1 ,24316.9 ,314.3,313.3,310.5
XS GIS Cut Line= 4
     1529962.691      355683.436     1529745.677      355672.586
     1529648.021      355702.968     1529428.837      355904.791
#Sta/Elev= 30
       0  935.75    47.2   924.8    94.5   912.8   103.9  910.66   141.7  902.71
   151.2  900.96   160.6   899.4   198.4  893.76   207.8  891.98   217.3  889.53
   226.6  886.57   235.9  882.01   245.2  875.71   254.5  869.73   262.1867.7372
   263.8  867.29   273.1  867.92   282.4  871.12   291.7  875.36     301  879.42
   310.3  882.41   319.6  884.27   406.1  895.84   415.7  898.08   434.9  904.74
   444.5  906.92   473.3  912.03   540.6  923.63   579.1  928.85   617.5  933.62
#Mann= 3 , 0 , 0
       0      .1       0   262.1    .045       0   273.1      .1       0
Bank Sta=262.1,273.1
XS Rating Curve= 0 ,0
Exp/Cntr=0.3,0.1

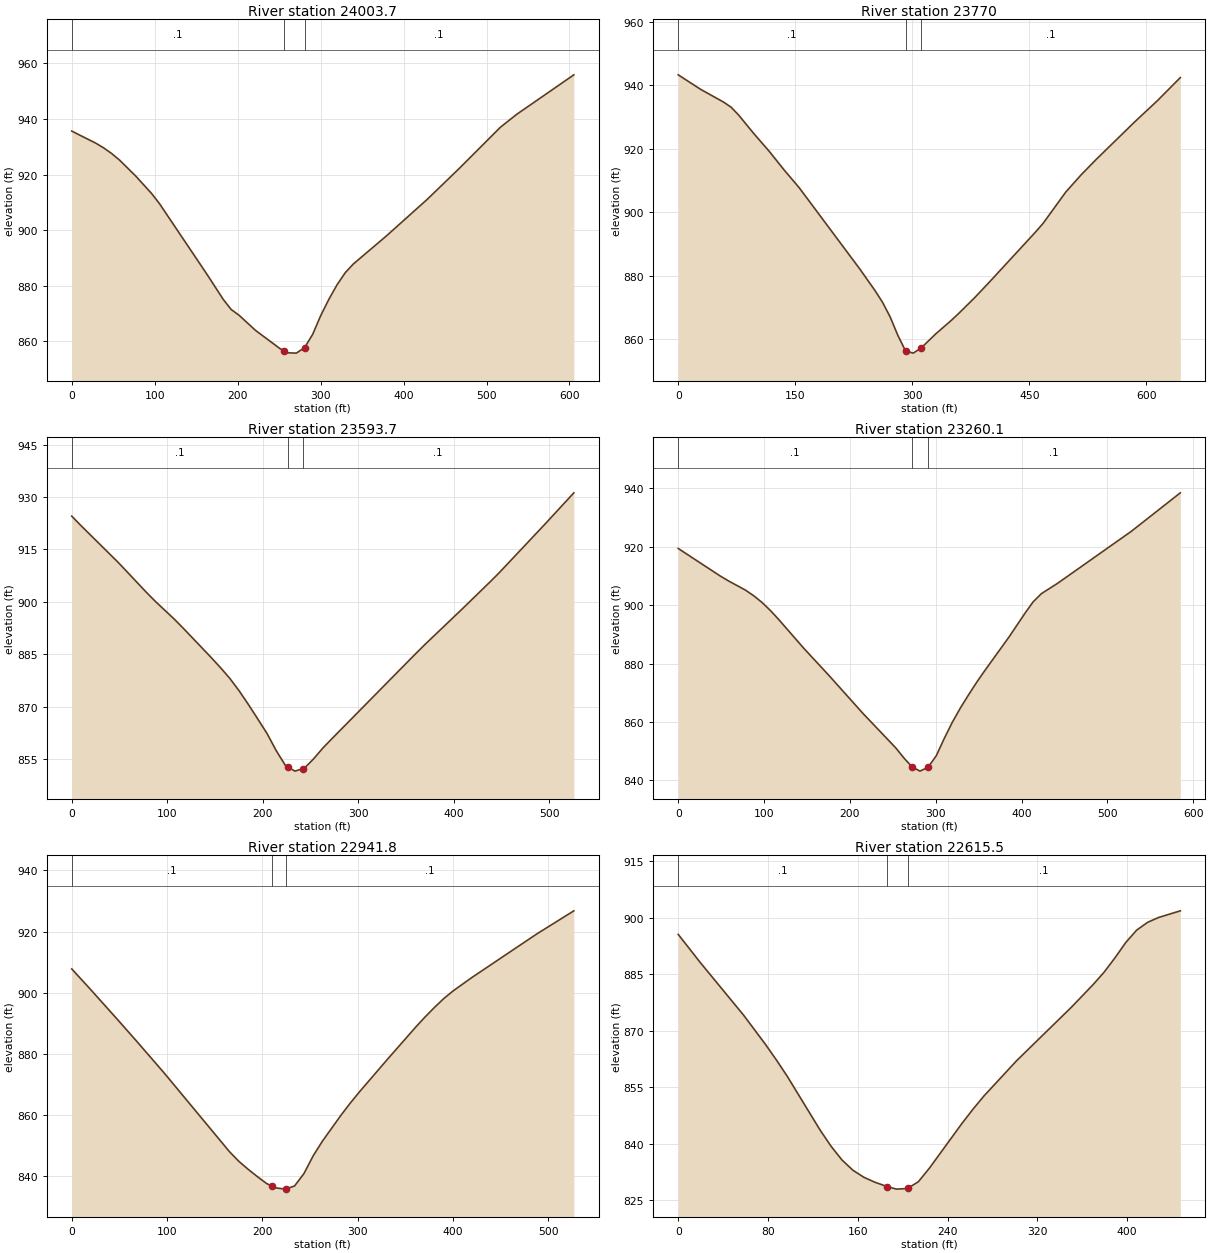
Type RM Length L Ch R = 1 ,24003.7 ,236.8,233.7,230.6
XS GIS Cut Line= 3
     1529875.886      355444.721     1529682.743      355386.127
      1529311.65      355544.548
#Sta/Elev= 30
       0  935.63    28.8  931.32    38.4   929.6    48.1  927.56    57.7  925.17
    76.9  919.51    96.1  913.22   105.7  909.53   163.4  883.89   182.6  875.04
   192.2  871.39   201.8   869.3   221.5  863.88     251  857.31   256.2  856.51
   260.9  855.79   270.7  855.68   280.6  857.63   290.4  862.42   300.2  869.24
   310.1  875.14   319.9  880.33   329.8  884.68   339.6  887.82     379   897.8
   428.2  910.96   467.6  922.33   516.8  937.04   536.4  941.67   605.3   955.9
#Mann= 3 , 0 , 0
       0      .1       0   256.2    .045       0   280.6      .1       0
Bank Sta=256.2,280.6
XS Rating Curve= 0 ,0
Exp/Cntr=0.3,0.1

Type RM Length L Ch R = 1 ,23770   ,177.4,176.3,174.9
XS GIS Cut Line= 3
     1529869.375      355192.985     1529608.959      355164.773
     1529281.268      355360.086
#Sta/Elev= 30
       0  943.22    29.1  938.59    58.2  934.62    67.9  932.99    77.6   930.5
      97  924.67   116.4  919.19   135.8  913.23   155.2  907.61   232.8  882.02
   252.2  875.25   261.9  871.54   271.7   866.9   281.5  861.12   291.3  856.27
   301.1  855.56   310.8  857.08   330.4  861.71     350  865.89   359.8  868.16
   379.3  872.88   398.9  877.98   457.6  893.63   467.4  896.38   496.7  906.32
   516.3  911.72   535.8  916.62   584.7  928.34   614.1  935.09   643.4  942.35
#Mann= 3 , 0 , 0
       0      .1       0   291.3    .045       0   310.8      .1       0
Bank Sta=291.3,310.8
XS Rating Curve= 0 ,0
Exp/Cntr=0.3,0.1

Type RM Length L Ch R = 1 ,23593.7 ,340.2,333.6,326.1
XS GIS Cut Line= 2
     1529671.893      354910.867     1529240.035      355210.346
#Sta/Elev= 30
       0   924.5     9.7  921.78    48.7  911.24    77.9  902.76    87.6  900.08
     107  895.11   116.8   892.4     146  884.02   155.7  881.14   165.4  878.08
   175.2  874.51   184.9  870.59   194.6  866.49   204.4  862.29   214.1  857.34
   223.8  853.08   226.6  852.64   233.6  851.53   241.6  852.21   243.3  852.35
     253     855   262.8  858.13   272.5  860.87   360.1  885.18   369.8  887.81
   408.8  897.98     438  905.74   447.7   908.4   496.3  922.52   525.5  931.18
#Mann= 3 , 0 , 0
       0      .1       0   226.6    .045       0   241.6      .1       0
Bank Sta=226.6,241.6
XS Rating Curve= 0 ,0
Exp/Cntr=0.3,0.1

Type RM Length L Ch R = 1 ,23260.1 ,335.4,318.3,299.1
XS GIS Cut Line= 4
     1529489.601      354743.766     1529259.566      354789.339
     1529142.379      354936.909     1529092.466      355090.989
#Sta/Elev= 30
       0  919.43    48.9     910    58.6   908.3    78.2  905.18    87.9  903.23
    97.7  900.91   107.5  898.13   117.2  895.04   146.6  885.11   175.9  875.81
     215  862.96   253.4  851.09   262.8  847.67   272.2  844.62   281.6  843.12
     291  844.43   300.5  848.33   309.9   854.3   319.3  859.87   328.7  864.75
   338.2  869.27   347.6  873.53     357  877.52   385.3  889.07   404.1   897.3
   413.5  901.15     423  903.93     442   907.5   527.8   925.3   584.9   938.5
#Mann= 3 , 0 , 0
       0      .1       0   272.2    .045       0     291      .1       0
Bank Sta=272.2,291
XS Rating Curve= 0 ,0
Exp/Cntr=0.3,0.1

Type RM Length L Ch R = 1 ,22941.8 ,330.5,326.2,321.6
XS GIS Cut Line= 3
     1528916.684      354505.051     1528964.427      354693.853
      1529003.49      355023.714
#Sta/Elev= 30
       0  907.78    19.5  901.14    48.7  890.98    68.2  884.08    97.4  873.57
   165.5  847.97   175.3  844.82     185  842.23   194.8   839.8   204.5  837.54
   210.3  836.69   214.3  836.11     224  835.71   225.3  835.85   233.8  836.74
   243.6  840.77   253.4  846.64   263.1  851.44   282.7  859.97   292.4  863.93
   302.2  867.65   331.5  878.28   360.8  888.69   370.6     892   380.4  895.11
   390.1     898   399.9  900.52   419.4  904.87   487.8  919.19   526.9   926.8
#Mann= 3 , 0 , 0
       0      .1       0   210.3    .045       0   225.3      .1       0
Bank Sta=210.3,225.3
XS Rating Curve= 0 ,0
Exp/Cntr=0.3,0.1

Type RM Length L Ch R = 1 ,22615.5 ,293.3,296.5,297.4
XS GIS Cut Line= 2
     1528593.334      354607.048     1528732.223      355032.395
#Sta/Elev= 30
       0  895.57    19.4  888.19    58.4  874.07    77.8  866.34    87.5  862.23
    97.3  857.83   126.4  843.64   136.2  839.33   145.9  835.69   155.6  832.98
   165.4   831.1   175.1   829.8   186.4  828.61   194.5  827.95   204.3  828.12
     214  829.92   223.7  833.47   252.9  845.41   262.6  849.15   272.4  852.67
   301.5  862.03   350.2  876.19   369.6  882.21   379.4   885.5   389.1  889.31
   398.8  893.41   408.5   896.7   418.3  898.77     428  900.05   447.4  901.82
#Mann= 3 , 0 , 0
       0      .1       0   186.4    .045       0   204.3      .1       0
Bank Sta=186.4,204.3
XS Rating Curve= 0 ,0
Exp/Cntr=0.3,0.1

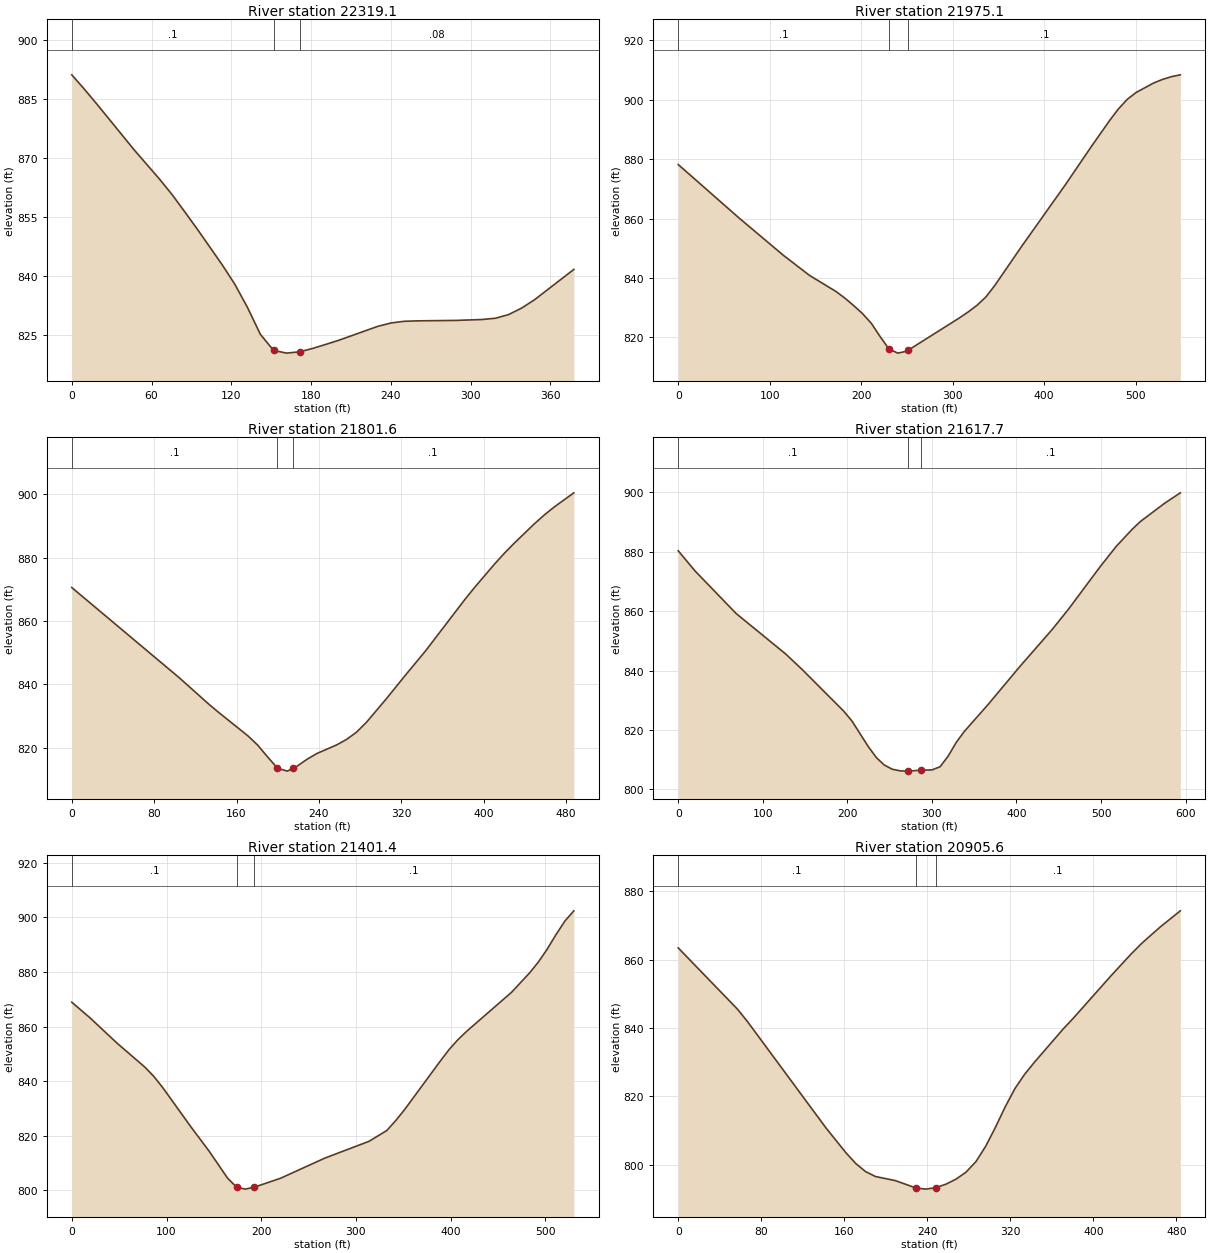
Type RM Length L Ch R = 1 ,22319.1 ,344.4,344,342.4
XS GIS Cut Line= 3
     1528402.361        354639.6     1528369.809      354767.638
     1528417.552      355008.523
#Sta/Elev= 29
       0  891.04     9.4  887.42    18.9   883.6    47.2  871.86    66.1   864.5
    75.5  860.58    84.9  856.26    94.4  851.83   113.2  842.73   122.7  837.78
   132.1  831.96   141.9  825.06   151.8  820.99   161.6  820.29   171.4  820.63
   181.2  821.48     191   822.5   200.9  823.56   230.3  827.11   240.2  827.96
     250  828.38   259.8  828.49   289.3  828.61   308.9  828.84   318.8  829.16
   328.6  830.09   338.4  831.73   348.2  833.88   377.7  841.57
#Mann= 3 , 0 , 0
       0      .1       0   151.8    .045       0   171.4     .08       0
Bank Sta=151.8,171.4
XS Rating Curve= 0 ,0
Exp/Cntr=0.3,0.1

Type RM Length L Ch R = 1 ,21975.1 ,174.3,173.5,172.4
XS GIS Cut Line= 3
     1527940.122      354654.791     1528020.417      354784.999
     1528115.903      355169.114
#Sta/Elev= 30
       0  878.18    66.9  860.08   114.7  847.69   143.4  840.88   172.3  835.48
   181.9  833.28   191.6  830.75   201.2  828.08   210.9   824.8   220.6  820.31
   230.2  816.17   239.9   814.7   249.5  815.33   251.5   815.7   307.4  826.57
   317.1   828.6   326.7  830.83   336.4  833.64     346  837.46     375  850.47
   423.3  871.44   452.2  884.53   471.6  893.02   481.2  896.93   490.9  900.15
   500.5  902.44   519.8  905.65   529.5  906.85   539.1  907.76   548.8  908.38
#Mann= 3 , 0 , 0
       0      .1       0   230.2    .045       0   251.5      .1       0
Bank Sta=230.2,251.5
XS Rating Curve= 0 ,0
Exp/Cntr=0.3,0.1

Type RM Length L Ch R = 1 ,21801.6 ,183.4,183.8,184
XS GIS Cut Line= 3
     1527800.611      354742.222     1527870.055      354898.472
     1527959.031      355202.291
#Sta/Elev= 30
       0  870.52   104.5  842.01     133  833.73   142.5  831.14     171  823.72
   180.6  820.76   190.2  817.04   199.5   813.6   199.8  813.49   209.4  812.56
   214.5  813.41     219  814.16   228.6  816.33   238.1  818.13   257.3  820.84
   266.9  822.57   276.5  824.84   286.1  827.94   305.3  835.32   324.5  843.04
   343.7  850.56     382  866.85   391.6   870.7   410.8  878.01   420.4  881.43
     430  884.61   449.2  890.62   458.8   893.4   468.4  895.91   487.6  900.42
#Mann= 3 , 0 , 0
       0      .1       0   199.5    .045       0   214.5      .1       0
Bank Sta=199.5,214.5
XS Rating Curve= 0 ,0
Exp/Cntr=0.3,0.1

Type RM Length L Ch R = 1 ,21617.7 ,220.8,216.4,212.8
XS GIS Cut Line= 4
     1527703.577      354713.384     1527688.386      354928.228
     1527729.618      355073.627     1527883.698      355240.728
#Sta/Elev= 30
       0  880.28    19.6  873.58    68.5  859.17   127.3  845.51   146.8  840.28
   195.8  826.32   205.6  822.95   224.8   814.4   234.3  810.73   243.7   808.2
   253.2   806.8   262.6  806.24   271.9806.1608     272  806.16   286.9 806.473
   300.4  806.59   309.8  807.66   319.3  811.24   328.7  815.78   338.2  819.46
   366.5  828.58   404.4  841.47   442.3  853.81   461.2  860.51   499.1  874.96
     518  881.75     537  887.54   546.5   890.1   574.9  896.19   593.8  899.77
#Mann= 3 , 0 , 0
       0      .1       0   271.9    .045       0   286.9      .1       0
Bank Sta=271.9,286.9
XS Rating Curve= 0 ,0
Exp/Cntr=0.3,0.1

Type RM Length L Ch R = 1 ,21401.4 ,492,495.8,496
XS GIS Cut Line= 4
     1527386.736      354923.888     1527497.414      355045.416
     1527564.688      355199.495     1527562.518      355396.978
#Sta/Elev= 30
       0  868.93    19.3  863.19    48.3  853.78    77.4  845.09      87  841.61
    96.7  837.34   125.7  823.32     145  814.38   164.4  804.54   173.7  801.28
   174.6   801.2     183  800.48   192.4  801.16   220.4  804.46   267.1  811.83
   313.8  817.99   332.5  821.93   341.9  825.55   351.3  829.58   388.9  847.32
   398.3  851.59   407.7  855.23   417.1  858.35   464.2  872.54     483  879.55
   492.4  883.56   501.8  888.33   511.2   893.7   520.6  898.66     530  902.39
#Mann= 3 , 0 , 0
       0      .1       0   174.6    .045       0   192.4      .1       0
Bank Sta=174.6,192.4
XS Rating Curve= 0 ,0
Exp/Cntr=0.3,0.1

Type RM Length L Ch R = 1 ,20905.6 ,269.4,267.4,266.1
XS GIS Cut Line= 4
     1527113.299      355010.693     1527052.535      355190.815
     1527085.087      355281.961     1527174.063      355457.742
#Sta/Elev= 30
       0  863.46      57  845.56    66.5     842   142.6  810.69   161.6  803.52
   171.1  800.36   180.6  797.98   190.1  796.56   209.4  795.34   228.8  793.23
   238.5  792.86   248.2  793.28   257.8  794.28   267.5  795.74   277.2  797.78
   286.9   800.9   296.3  805.39   305.6  810.87     315  816.85   324.4  822.24
   333.8  826.45   343.2  829.96   371.3  839.83   380.7  842.86   418.2  855.67
     437  861.84   446.4   864.7   455.8  867.25   465.1  869.72   483.9  874.31
#Mann= 3 , 0 , 0
       0      .1       0   228.8    .045       0   248.2      .1       0
Bank Sta=228.8,248.2
XS Rating Curve= 0 ,0
Exp/Cntr=0.3,0.1

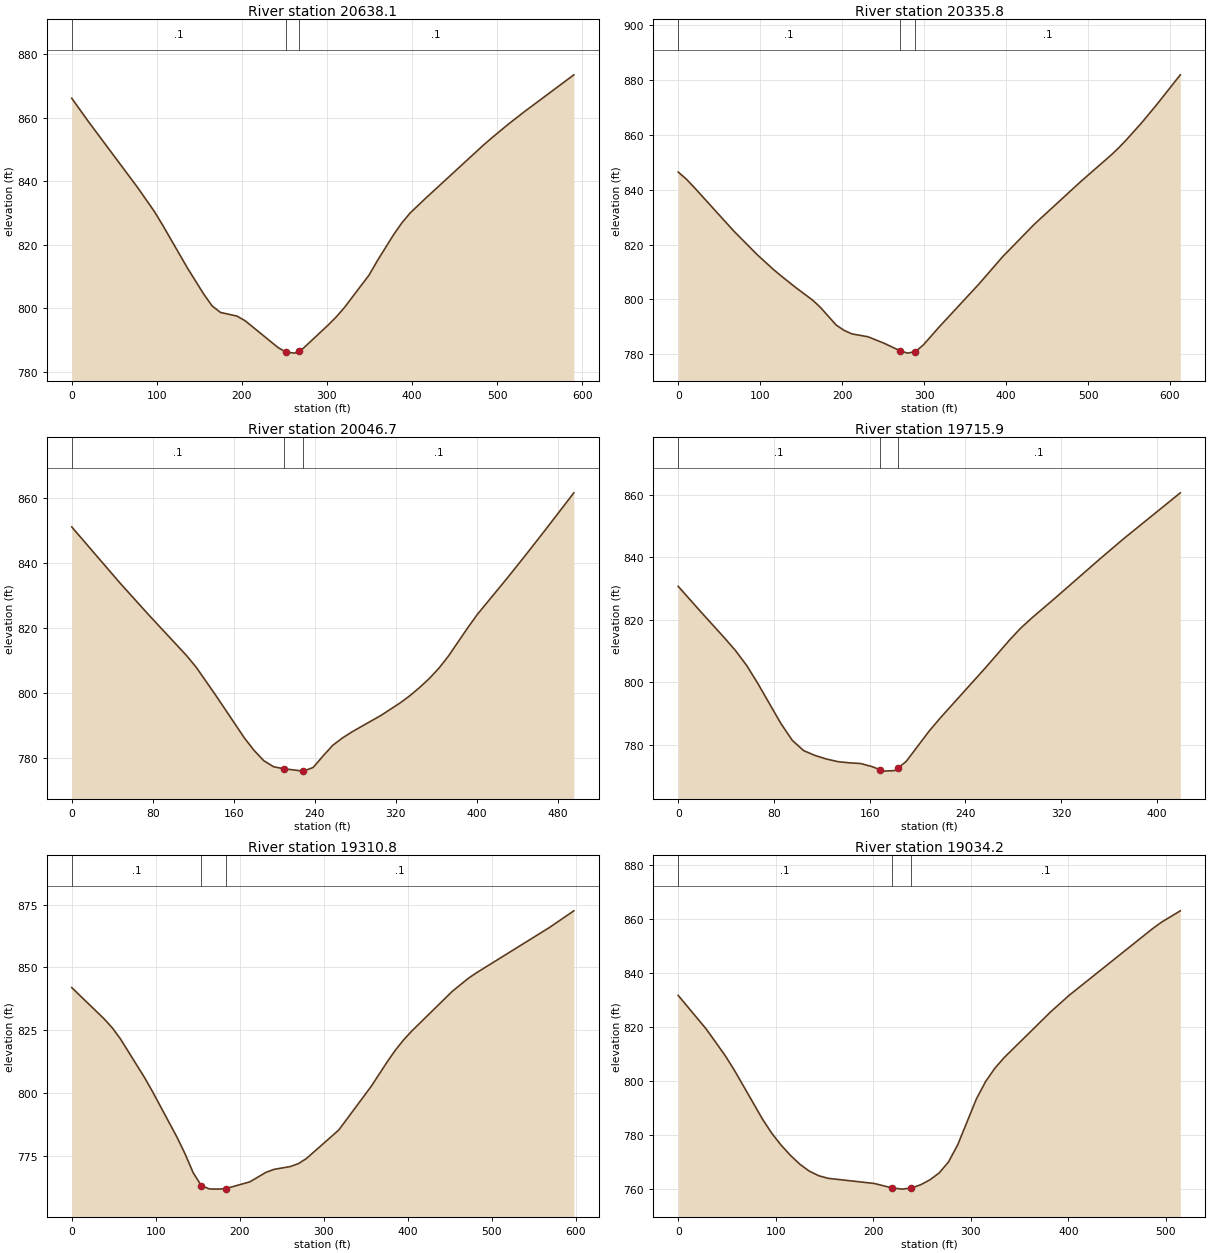
Type RM Length L Ch R = 1 ,20638.1 ,300.7,302.3,302.4
XS GIS Cut Line= 3
     1526709.653      355090.989     1526857.223      355407.829
     1527072.066      355516.336
#Sta/Elev= 30
       0  866.15    19.4  858.89    77.7  837.95    97.1   830.5   106.8  826.24
   135.9  812.74   155.3  804.42     165  800.76   174.8  798.72   194.2  797.56
   203.9  796.08   242.7  787.61   251.6  786.25   262.1   785.9   266.6  786.57
   271.8  787.34     301  794.64   310.7  797.25   320.4  800.22   349.5  810.49
   359.2  814.98   378.4  823.24     388   826.9   397.7  830.02   416.9   834.9
   484.3   851.5   493.9  853.72   513.2     858   532.4     862   590.2  873.54
#Mann= 3 , 0 , 0
       0      .1       0   251.6    .045       0   266.6      .1       0
Bank Sta=251.6,266.6
XS Rating Curve= 0 ,0
Exp/Cntr=0.3,0.1

Type RM Length L Ch R = 1 ,20335.8 ,288.7,289.1,288.6
XS GIS Cut Line= 4
      1526355.92      355255.919     1526520.851      355373.107
     1526614.167       355585.78     1526618.507      355763.732
#Sta/Elev= 30
       0  846.43     9.6  843.95    19.3  840.91    67.4  825.04    96.3   816.3
   115.6  811.04   125.2  808.62   144.5  804.04   163.8  799.75   173.4  797.08
   192.7  790.62   202.3  788.67     212  787.37   231.4  786.34   250.7  784.03
   270.1  781.31   279.7  780.36   289.4  780.91   299.1  783.36   318.4  789.92
   366.8  805.54   395.9  815.57   434.6  827.43   490.8  842.88   528.3  852.68
   537.6  855.33     547  858.27   565.7  864.51   584.5   871.3   612.6  881.92
#Mann= 3 , 0 , 0
       0      .1       0   270.1    .045       0   289.4      .1       0
Bank Sta=270.1,289.4
XS Rating Curve= 0 ,0
Exp/Cntr=0.3,0.1

Type RM Length L Ch R = 1 ,20046.7 ,326.9,330.8,333.5
XS GIS Cut Line= 4
     1526160.608      355379.617     1526277.795      355516.336
     1526312.518      355596.631     1526455.747      355774.582
#Sta/Elev= 30
       0  851.04    47.4  833.86    75.8  824.04   113.7  811.33   123.2  807.72
   142.2  799.21   170.6  786.03   180.1  782.23   189.8  779.02   199.5  777.18
   209.2  776.59   228.7  775.84   238.4  776.95   248.1  780.46   257.8  783.79
   267.6  786.09   277.1  787.98   305.6  793.02   324.7  796.91   334.2  799.12
   343.7  801.62   353.2  804.35   362.7  807.54   372.2  811.31   391.3  820.04
   400.8  824.16   429.4  834.98   448.4  842.39   467.4  849.96     496  861.55
#Mann= 3 , 0 , 0
       0      .1       0   209.2    .045       0   228.7      .1       0
Bank Sta=209.2,228.7
XS Rating Curve= 0 ,0
Exp/Cntr=0.3,0.1

Type RM Length L Ch R = 1 ,19715.9 ,403.3,405.1,405.5
XS GIS Cut Line= 3
     1525976.146      355509.825     1526028.229      355702.968
     1526119.375       355902.62
#Sta/Elev= 30
       0  830.73      19  822.52    38.1  814.43    47.6  810.26    57.2  805.36
    66.7  799.47    85.7   786.8    95.3  781.35   104.8  778.05   114.3   776.5
   123.8  775.37   133.4  774.52   142.9  774.14   152.4  773.92   161.9  772.94
   168.5  771.94   171.5  771.48     181  771.65   183.5  772.43   190.5   774.6
   209.6   784.3   219.1  788.59   257.3  804.88   276.4  813.34   285.9  817.24
   295.5  820.61   314.6  826.87   352.7  839.65   371.8  845.89   419.5  860.72
#Mann= 3 , 0 , 0
       0      .1       0   168.5    .045       0   183.5      .1       0
Bank Sta=168.5,183.5
XS Rating Curve= 0 ,0
Exp/Cntr=0.3,0.1

Type RM Length L Ch R = 1 ,19310.8 ,272.8,276.6,279.9
XS GIS Cut Line= 4
     1525618.073      355592.291     1525626.754      355726.839
     1525663.646       355896.11     1525919.723      356030.659
#Sta/Elev= 30
       0  841.95    38.5  829.52    48.2  825.95    57.8  821.59    86.7  806.09
    96.3  800.43   125.2  782.41   134.8  775.79   144.4   768.3   154.1  763.14
   163.7   761.8   173.3  761.73     183  761.91   211.8  764.62   231.1  768.41
   240.7   769.6     260  770.72   269.6  771.88   279.2  773.91   317.7  785.27
   356.3  802.65   375.6  812.54   385.2  817.13   394.8  821.12   404.5  824.65
   452.7  840.45     472  845.69   481.6  847.86   568.4  865.89   597.4  872.52
#Mann= 3 , 0 , 0
       0      .1       0   154.1    .045       0     183      .1       0
Bank Sta=154.1,183
XS Rating Curve= 0 ,0
Exp/Cntr=0.3,0.1

Type RM Length L Ch R = 1 ,19034.2 ,221.9,209.4,196.3
XS GIS Cut Line= 4
     1525442.292       355579.27     1525357.657      355707.308
     1525366.337      355859.218      1525411.91      356063.211
#Sta/Elev= 30
       0  831.73    28.8  819.24      48  809.52    57.6  804.01    86.3  785.99
    95.9  780.69   105.5  776.29   115.1  772.49   124.7  769.22   134.3  766.68
   143.9  764.99   153.5  764.02     201   762.1   219.2  760.45   229.6  760.01
   239.1  760.43   248.6  761.64   258.1  763.47   267.6  766.04   277.1  770.09
   286.6   776.5   305.6  793.36   315.1  799.85   324.6  804.78   334.1   808.7
   381.6  825.58   400.6  831.73   486.2  856.43   495.7  858.91   514.7  863.05
#Mann= 3 , 0 , 0
       0      .1       0   219.2    .045       0   239.1      .1       0
Bank Sta=219.2,239.1
XS Rating Curve= 0 ,0
Exp/Cntr=0.3,0.1

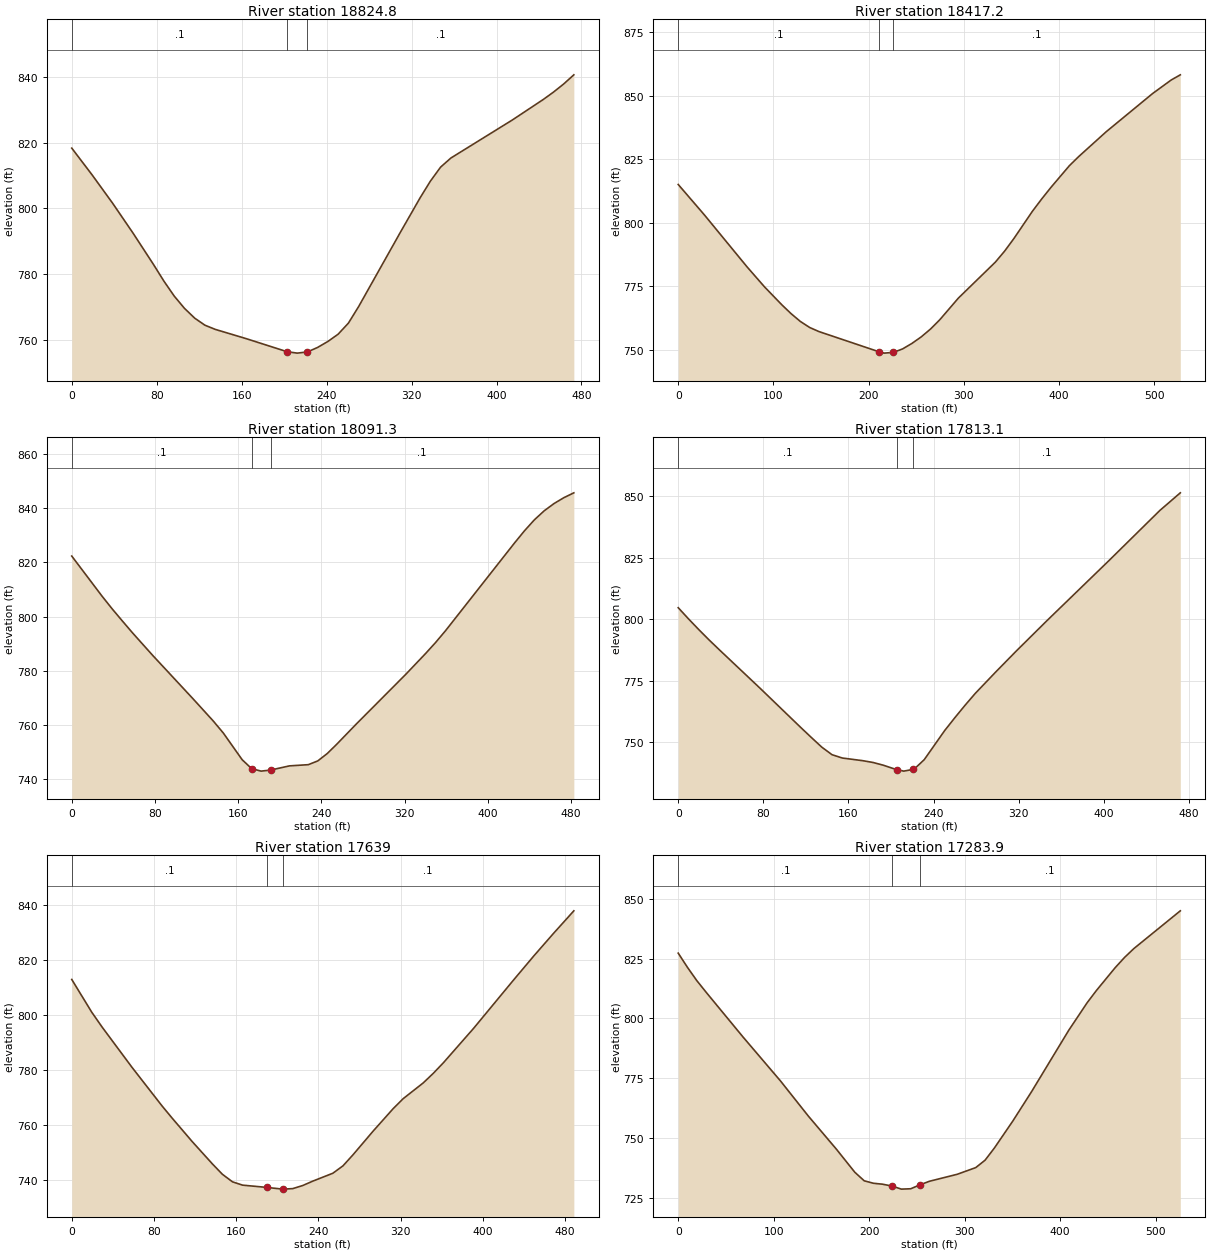
Type RM Length L Ch R = 1 ,18824.8 ,397.4,407.6,417.4
XS GIS Cut Line= 2
     1525032.136      355635.693     1525307.743      356019.808
#Sta/Elev= 30
       0  818.33    19.3  810.11    38.6  801.48    57.9  792.33    77.2  782.75
    86.8  777.78    96.5  773.23   106.1  769.51   115.8   766.5   125.4  764.36
   135.1  763.09     164  760.29   202.6   756.3   212.3  755.85   221.9  756.21
   231.6   757.6   241.2  759.41   250.8  761.61   260.5  764.99   270.2  770.07
   308.7  792.25     328  803.17   337.7  808.26   347.3  812.53     357  815.31
   414.9  826.91   443.8  833.11   453.5  835.37   463.1  837.84   472.8  840.67
#Mann= 3 , 0 , 0
       0      .1       0   202.6    .045       0   221.9      .1       0
Bank Sta=202.6,221.9
XS Rating Curve= 0 ,0
Exp/Cntr=0.3,0.1

Type RM Length L Ch R = 1 ,18417.2 ,327.7,325.9,323
XS GIS Cut Line= 4
     1524739.167        355744.2      1524791.25      355839.686
     1524810.782      356004.617     1524973.542      356197.759
#Sta/Elev= 30
       0  815.11    27.2  803.26    72.5  782.58    90.6  774.81   108.8  767.74
   118.5  764.26   128.3  761.17   138.1  758.79   147.8  757.19     211  749.22
   216.2   748.7     226  748.98   235.8  750.38   245.5  752.53   255.3  755.11
   265.1  758.21   274.8  761.87   294.3  770.38   333.1  784.53   342.8  788.85
   352.6  793.83     372  804.54   381.7  809.36   391.4  813.92   410.8  822.48
   420.6  826.09   449.7  835.93   498.3  850.93   517.7  856.23   527.4   858.3
#Mann= 3 , 0 , 0
       0      .1       0     211    .045       0     226      .1       0
Bank Sta=211,226
XS Rating Curve= 0 ,0
Exp/Cntr=0.3,0.1

Type RM Length L Ch R = 1 ,18091.3 ,279.9,278.1,276
XS GIS Cut Line= 4
     1524500.452      355726.839     1524491.771      355872.239
     1524515.643      355978.575     1524511.302       356206.44
#Sta/Elev= 30
       0  822.32    29.1  807.55    38.8  802.88    48.6  798.42    58.3  794.07
    77.7  785.76   116.5  769.75     136  761.55   145.7   757.1   163.8  747.27
   172.9  743.99     182  743.07   191.1  743.46   209.2     745   227.4  745.45
   236.5  746.84   245.6  749.56   254.6  752.94   273.6  760.47   321.1  778.76
   340.1  786.41   349.6  790.42   359.1  794.74   425.6  827.16   435.1  831.61
   444.6  835.65   454.1     839   463.6  841.69     473  843.84   482.6  845.63
#Mann= 3 , 0 , 0
       0      .1       0   172.9    .045       0   191.1      .1       0
Bank Sta=172.9,191.1
XS Rating Curve= 0 ,0
Exp/Cntr=0.3,0.1

Type RM Length L Ch R = 1 ,17813.1 ,176.5,174.1,170.7
XS GIS Cut Line= 3
     1524156.948      355783.889     1524215.541      355905.416
     1524317.538      356226.597
#Sta/Elev= 30
       0  804.74     9.6  800.23    19.3  795.85    28.9  791.68    38.6  787.65
    77.1  771.92   115.6  755.86   125.3   751.9   134.9  748.05   144.5  744.98
   154.2  743.62   173.4  742.54   183.1  741.81   192.7   740.7   202.3  739.32
   205.9  738.93   211.9  738.29   220.9     739   221.6  739.05   231.2  742.94
   250.4  754.77   260.1  760.07   269.7  765.13   279.3  769.95   298.6  778.69
   317.8  787.16   346.7  799.54   404.5  823.76   452.6  844.26   471.9  851.46
#Mann= 3 , 0 , 0
       0      .1       0   205.9    .045       0   220.9      .1       0
Bank Sta=205.9,220.9
XS Rating Curve= 0 ,0
Exp/Cntr=0.3,0.1

Type RM Length L Ch R = 1 ,17639   ,353.8,355.1,356.2
XS GIS Cut Line= 2
      1523999.15      355807.134     1524174.931      356262.864
#Sta/Elev= 30
       0   812.8    19.5  800.89    29.3  795.63    58.6   780.9    87.9  766.85
    97.7  762.44   117.2  753.93   136.8  745.84   146.5  742.08   156.3  739.34
   166.1  738.13   190.1  737.29   205.1  736.68   214.9  736.86   224.7  737.99
   234.5  739.59     254  742.45   263.8  745.13   273.5  749.11   293.1  757.72
   312.6  765.88   322.4  769.53   341.9  775.25   351.7  778.73   361.5  782.56
   390.8  795.02   429.8  812.63   449.4  821.32   468.9  829.65   488.4  837.73
#Mann= 3 , 0 , 0
       0      .1       0   190.1    .045       0   205.1      .1       0
Bank Sta=190.1,205.1
XS Rating Curve= 0 ,0
Exp/Cntr=0.3,0.1

Type RM Length L Ch R = 1 ,17283.9 ,409.8,412.8,415.1
XS GIS Cut Line= 2
     1523656.268      355880.919      1523851.58        356369.2
#Sta/Elev= 30
       0  827.24     9.7  821.29    19.5  815.74    29.2  810.91    68.2  792.04
   107.1  773.84   136.3  759.14   165.6  745.35     185  735.66   194.8   732.1
   204.5  731.07   214.2  730.67   224.3  729.87   233.7  728.62   243.5  728.77
   253.2  730.41     263  731.89   292.2  734.82   311.6  737.61   321.4  740.71
   331.1  745.77   350.6  757.16   370.1  769.36     409  794.98   428.5  806.62
   438.2  811.72   457.7  821.18   467.5  825.45   477.2  829.14   525.9  844.93
#Mann= 3 , 0 , 0
       0      .1       0   224.3    .045       0   253.2      .1       0
Bank Sta=224.3,253.2
XS Rating Curve= 0 ,0
Exp/Cntr=0.3,0.1