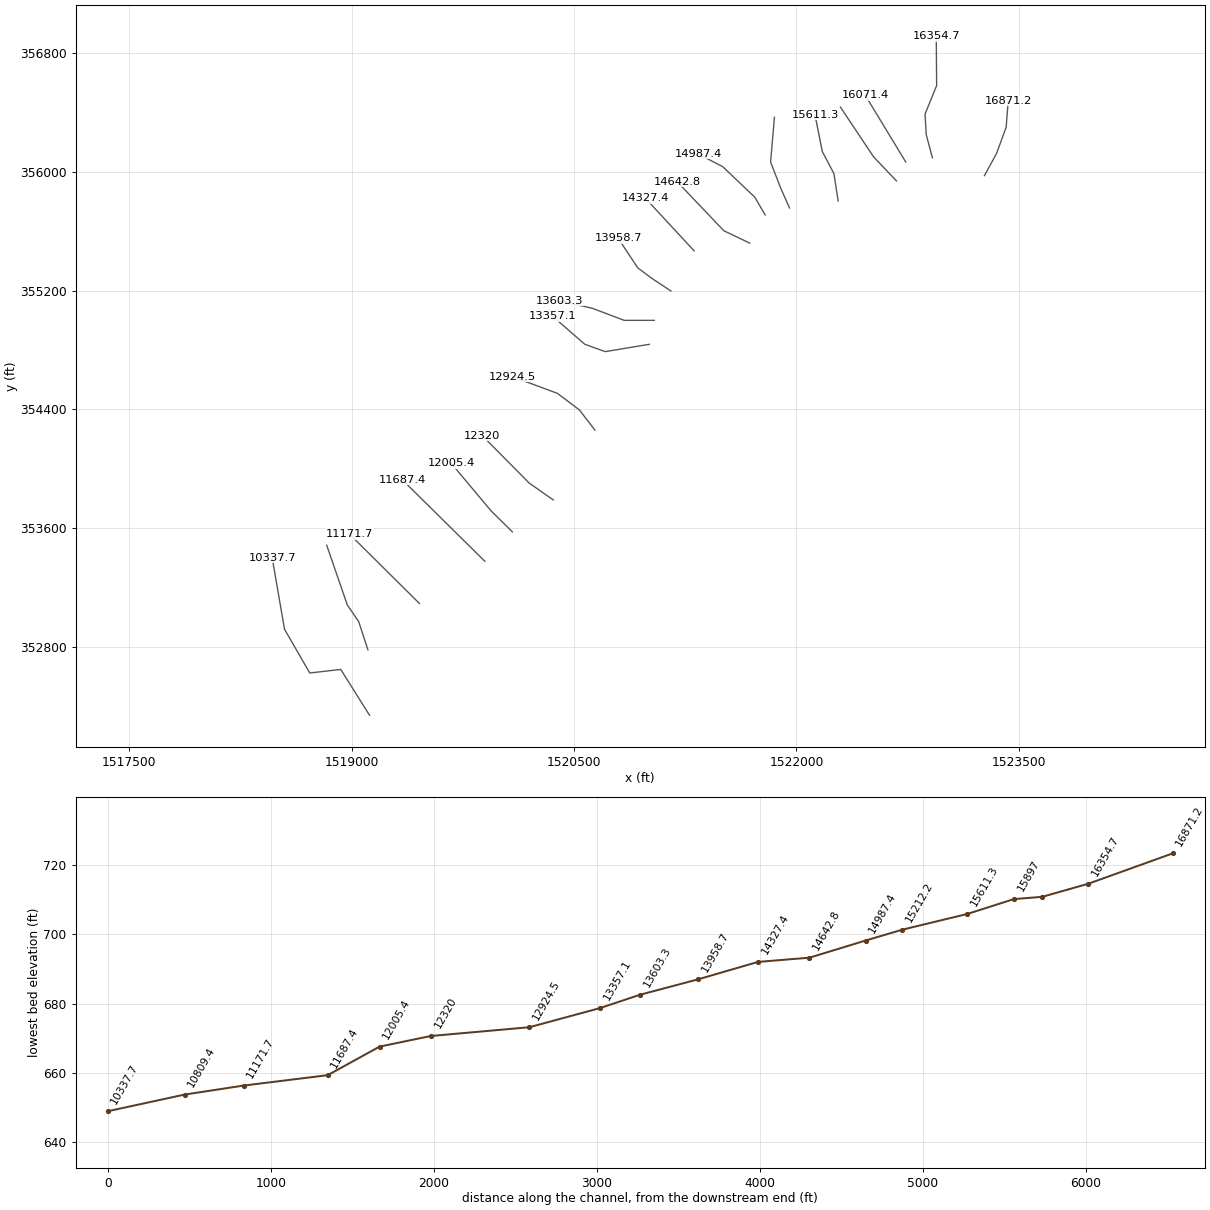
HEC-RAS study BENSRN.prj: BENSRN

--- BENSRN.g01 (geometry) --- (continued)

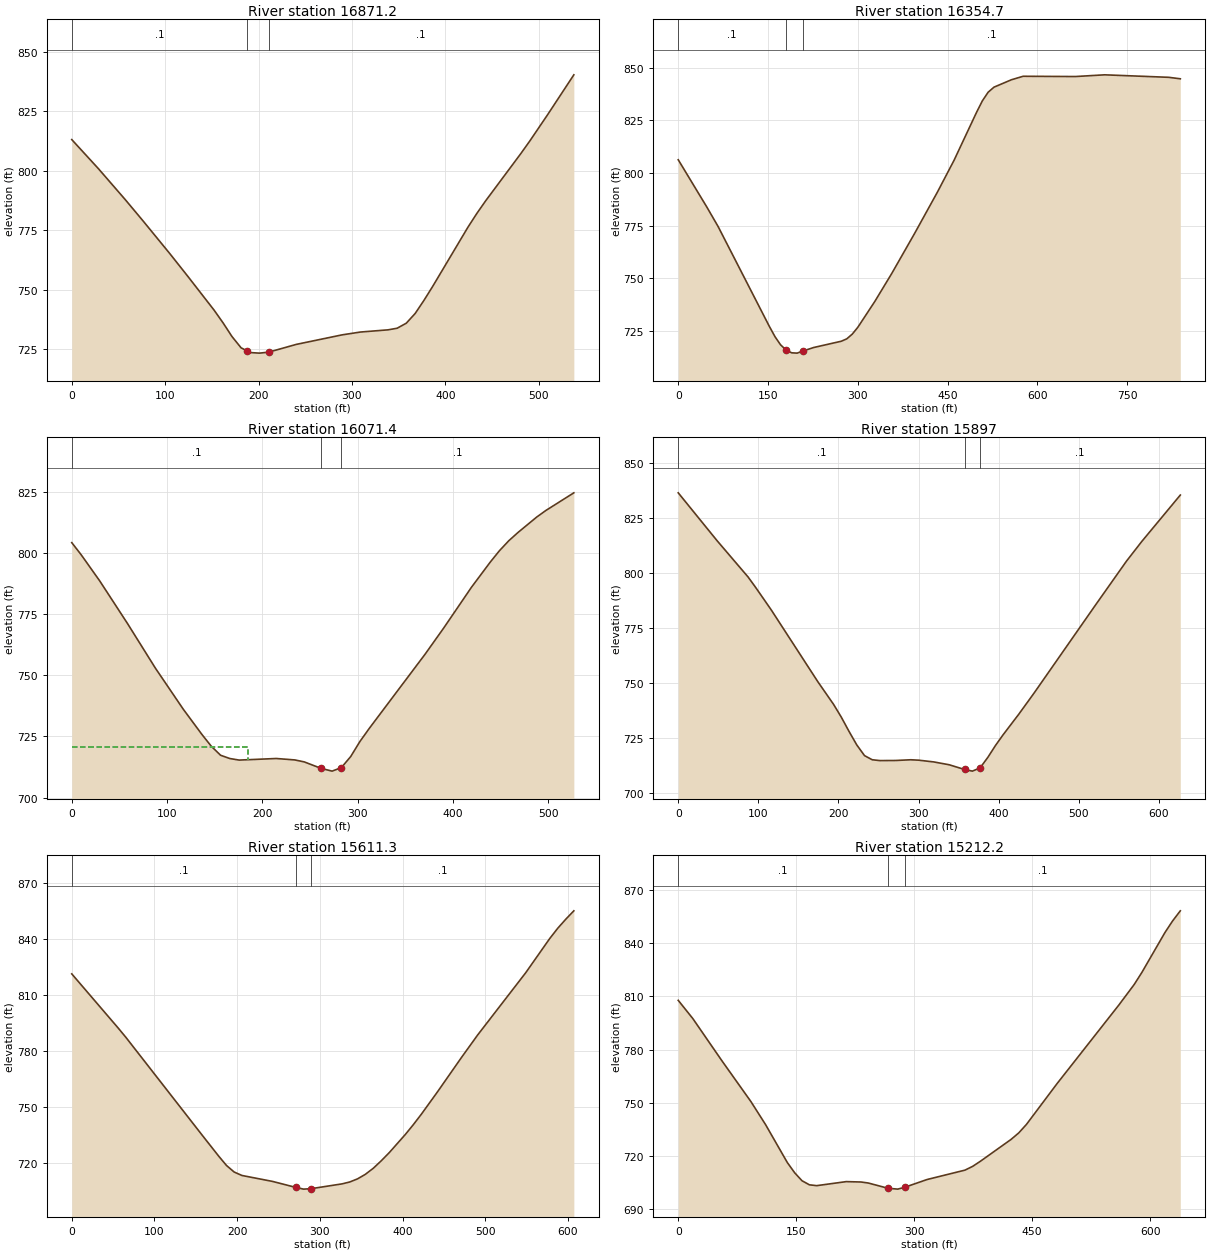
Type RM Length L Ch R = 1 ,16871.2 ,506.6,516.5,525
XS GIS Cut Line= 4
     1523267.813      355976.405     1523349.844      356127.013
      1523414.08       356302.36     1523427.969       356481.18
#Sta/Elev= 30
       0  813.05    28.6   800.8    57.2  787.86    76.2  778.94   104.8  765.23
   123.9  755.78   152.4  741.39     162  736.05   171.5  730.33   181.3  725.56
     188  724.21   191.2  723.56     201  723.33   210.8  723.73   240.3  726.99
   289.4     731   309.1  732.19   338.6  733.11   348.4  733.79   358.2  735.91
   367.7  739.99   377.1  745.49   386.6  751.46   424.3   776.3   433.8  782.06
   443.2  787.34     481  807.26   490.4  812.43   509.3  823.38   537.6  840.26
#Mann= 3 , 0 , 0
       0      .1       0     188    .045       0   210.8      .1       0
Bank Sta=188,210.8
XS Rating Curve= 0 ,0
Exp/Cntr=0.3,0.1

Type RM Length L Ch R = 1 ,16354.7 ,270.7,283.3,294.7
XS GIS Cut Line= 5
     1522916.684      356096.631     1522875.018      356252.881
     1522867.205      356390.902      1522945.33       356583.61
     1522942.726      356914.339
#Sta/Elev= 30
       0  806.31    47.6  783.96    66.6  774.64   152.2  727.26   161.7  722.35
   170.9  718.54   180.1  716.09   189.4  714.74   198.6  714.59   207.8  715.54
   226.2  717.25   272.3  720.23   281.5  721.36   290.7  723.61     300  726.86
   328.3  739.08   356.7   752.4   394.5  771.21   432.3  790.64   460.6     806
   498.4  828.87   507.9  834.21   517.6  838.32   527.4  840.74   556.5  844.25
     576   845.9   663.5  845.78   712.2  846.59   819.2  845.41   838.6  844.71
#Mann= 3 , 0 , 0
       0      .1       0   180.1    .045       0   207.8      .1       0
Bank Sta=180.1,207.8
XS Rating Curve= 0 ,0
Exp/Cntr=0.3,0.1

Type RM Length L Ch R = 1 ,16071.4 ,173.8,174.4,175.3
XS GIS Cut Line= 2
     1522736.997      356067.985     1522463.559      356518.506
#Sta/Elev= 30
       0  804.36     9.8  799.44    29.3  788.72    58.6  771.18    87.8  752.96
   117.1  736.12   136.6  725.83   146.4  721.01   156.2   717.3   165.9  715.96
   175.7  715.32   214.7  715.97   234.2  715.38     244  714.58   261.9   711.9
   273.3   710.8     283  712.25   292.8  716.78   302.5  722.96   312.3  728.31
   370.9   758.7   390.4   769.4   419.6  786.12   439.2  796.36   448.9  801.05
   458.7  805.13   468.4  808.53     488  814.83   497.7  817.55     527  824.76
#Mann= 3 , 0 , 0
       0      .1       0   261.9    .045       0     283      .1       0
#XS Ineff= 2 , 0
          185.09  720.78
Permanent Ineff=
       F       F
Bank Sta=261.9,283
XS Rating Curve= 0 ,0
Exp/Cntr=0.3,0.1

Type RM Length L Ch R = 1 ,15897   ,288.3,285.7,283
XS GIS Cut Line= 3
     1522674.497      355940.381     1522520.851      356101.839
     1522296.893      356437.777
#Sta/Elev= 30
       0  836.42    48.4  814.74    87.2  798.22    96.9  793.35   116.3  783.17
   174.4  750.62   193.8  740.47   203.5  734.64   213.2  728.14   222.9  721.99
   232.5  717.17   242.1   715.3   251.7  714.92     271  714.97   290.2  715.29
   299.8  715.12     319  714.31   338.2  713.02   357.3  710.89   367.1  710.14
   376.7  711.62   386.3  716.33   395.9  721.76   405.5  726.66   424.8  735.86
     444  745.51   520.9  785.58   559.3  805.36   578.6  814.39   626.6  835.41
#Mann= 3 , 0 , 0
       0      .1       0   357.3    .045       0   376.7      .1       0
Bank Sta=357.3,376.7
XS Rating Curve= 0 ,0
Exp/Cntr=0.3,0.1

Type RM Length L Ch R = 1 ,15611.3 ,401.8,399.1,395.9
XS GIS Cut Line= 4
     1522281.268      355804.964     1522252.622       355989.86
     1522174.497      356138.298     1522125.018      356385.693
#Sta/Elev= 30
       0  821.23    56.1  792.22    65.5  787.18     159  734.03   177.8  723.46
   187.1  718.53   196.4  715.01   205.7  713.18     243  709.96     271  706.76
   280.3  705.85   289.6   706.1   326.9  708.67   336.2  709.69   345.5  711.34
   354.8  713.72   364.6  717.03   374.2  721.03     384  725.46   403.4  735.18
   413.1  740.45   422.8  746.06   442.2  757.98   471.3  776.46   490.7  788.42
   548.9  821.84     578  840.21   587.7  845.72   597.4  850.55   607.1  855.03
#Mann= 3 , 0 , 0
       0      .1       0     271    .045       0   289.6      .1       0
Bank Sta=271,289.6
XS Rating Curve= 0 ,0
Exp/Cntr=0.3,0.1

Type RM Length L Ch R = 1 ,15212.2 ,214.5,224.8,234.6
XS GIS Cut Line= 4
     1521953.143      355758.089     1521893.247      355893.506
     1521825.539      356067.985      1521851.58      356370.068
#Sta/Elev= 30
       0  807.77    18.5  797.51    55.5  773.71    92.5  750.62     111  737.73
   138.8  716.24   148.1  710.51   157.4  706.03   166.8  703.74   176.1  703.27
   213.6  705.54   232.3  705.33   241.6  704.76   266.6  701.81   279.1  701.31
   288.4  702.41   316.5  706.74   364.6  712.02   374.4  714.16   384.1  716.99
   423.2  729.34     433  733.02   442.8  737.82   481.9  760.93   560.2  805.09
   579.8  816.72   589.5  823.48   618.9  846.02   628.6  852.53   638.4  858.24
#Mann= 3 , 0 , 0
       0      .1       0   266.6    .045       0   288.4      .1       0
Bank Sta=266.6,288.4
XS Rating Curve= 0 ,0
Exp/Cntr=0.3,0.1

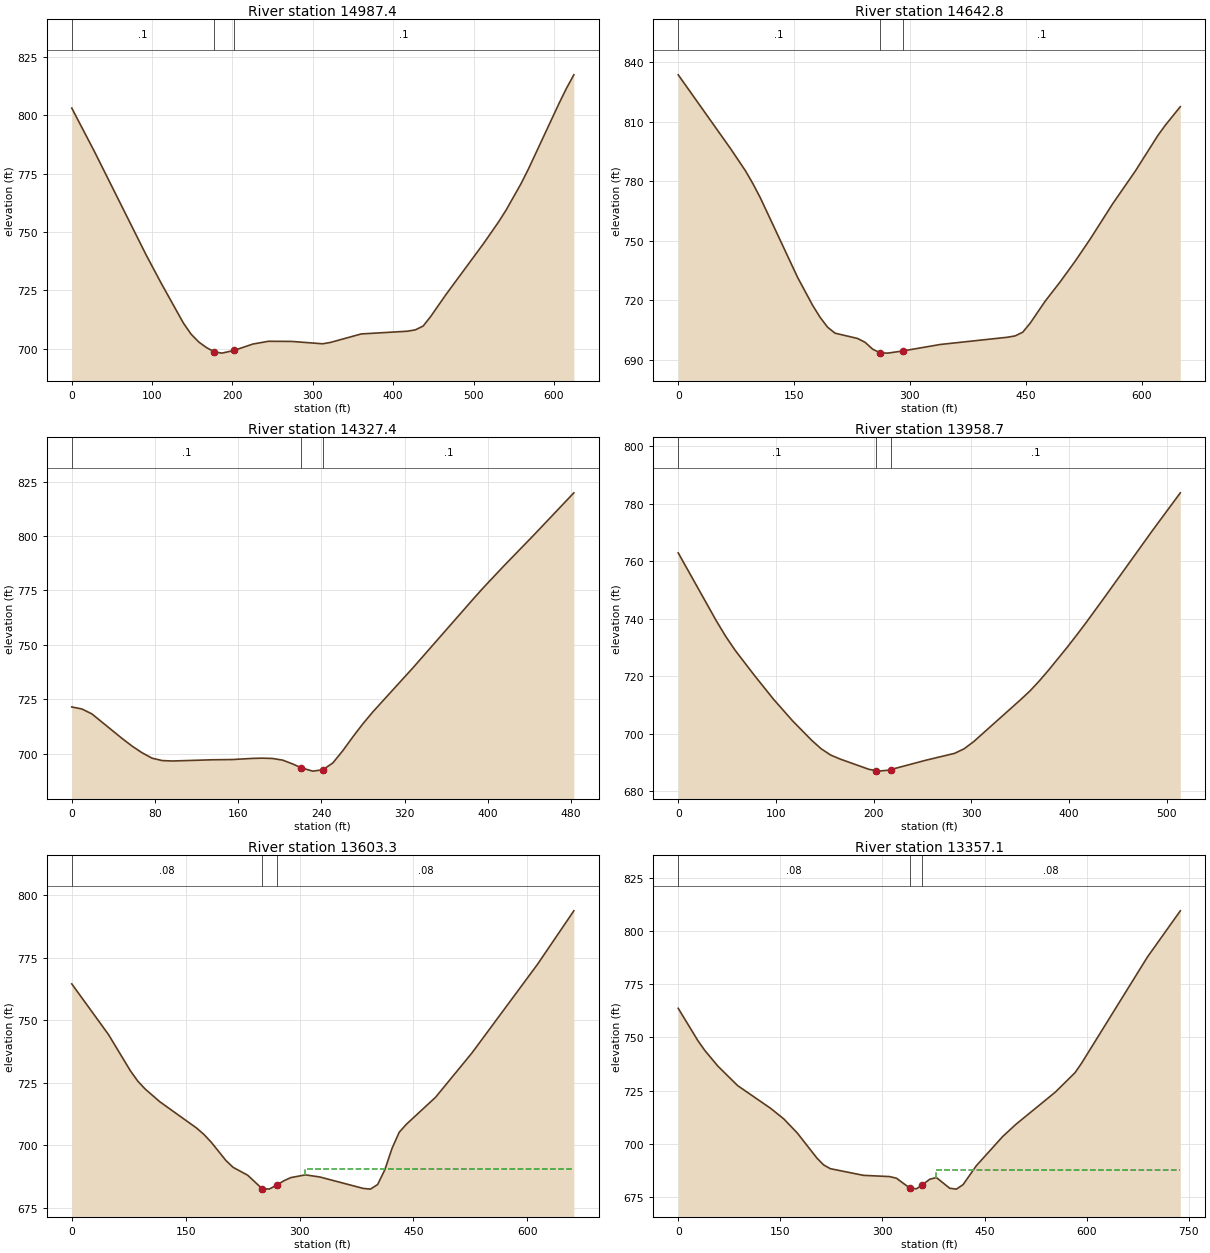
Type RM Length L Ch R = 1 ,14987.4 ,344.5,344.7,344.7
XS GIS Cut Line= 4
      1521789.08      355711.214     1521718.768      355831.006
     1521502.622      356036.735     1521335.955      356122.673
#Sta/Elev= 30
       0  803.12    27.8  784.78    92.6   740.2   111.1  728.24   138.9  711.07
   148.5   706.3   158.2   702.9   167.8  700.52   177.4  698.74   186.8  698.18
   201.8  699.31   225.5  702.08   244.8  703.25   273.7  703.19   312.2  702.18
   321.8  702.75   360.3   706.4     418  707.57   427.7  708.16   437.3  709.78
   446.7  713.89   465.4  723.14   512.3  745.05   531.1  754.35   540.4  759.39
   559.2  770.82   568.6  777.25   606.1  804.92   615.4  811.45   624.8  817.36
#Mann= 3 , 0 , 0
       0      .1       0   177.4    .045       0   201.8      .1       0
Bank Sta=177.4,201.8
XS Rating Curve= 0 ,0
Exp/Cntr=0.3,0.1

Type RM Length L Ch R = 1 ,14642.8 ,315.5,315.4,315.3
XS GIS Cut Line= 3
     1521684.914       355521.11     1521510.434      355604.443
      1521195.33      355935.173
#Sta/Elev= 30
       0  833.76    67.7  796.52      87  785.34    96.7  778.81   106.4  771.59
   154.7   731.4     174   717.4   183.7  711.33   193.4  706.33   203.1   703.3
   232.2  700.64     242  698.68   251.7  695.26   261.4   693.4   271.1  693.23
   290.6  694.31   339.2  697.59   426.6  701.26   436.3  701.94   446.1  703.78
   455.8  708.36   475.2  719.47   494.7  729.26   514.1  739.69   533.5  750.83
   562.7   768.7   591.8  785.08     621  803.05   630.7  808.27   650.2  817.68
#Mann= 3 , 0 , 0
       0      .1       0   261.4    .045       0   290.6      .1       0
Bank Sta=261.4,290.6
XS Rating Curve= 0 ,0
Exp/Cntr=0.3,0.1

Type RM Length L Ch R = 1 ,14327.4 ,364.3,368.7,372.9
XS GIS Cut Line= 2
     1521309.914      355469.027     1520981.789      355823.193
#Sta/Elev= 30
       0  721.48     9.7  720.56    19.3  718.31    48.3  707.05    57.9  703.54
    67.6  700.45    77.2  697.96    86.9  696.86    96.6  696.66   135.2  697.22
   154.5  697.33   173.8  697.86   183.5  697.96   193.1  697.82   202.8  697.06
   212.4  695.32   220.7  693.52   231.8  692.01   241.4  692.62   251.1  695.79
   260.7  701.44   270.4   707.8     280  713.79   289.7  719.31   328.3  739.58
   386.2  771.15   395.9  776.31   415.2  786.11   444.2  800.38   482.8  819.83
#Mann= 3 , 0 , 0
       0      .1       0   220.7    .045       0   241.4      .1       0
Bank Sta=220.7,241.4
XS Rating Curve= 0 ,0
Exp/Cntr=0.3,0.1

Type RM Length L Ch R = 1 ,13958.7 ,348.9,355.4,361.8
XS GIS Cut Line= 4
     1521153.664      355198.193     1521023.455      355284.131
     1520929.705      355354.443     1520796.893      355554.964
#Sta/Elev= 30
       0  762.91      39  739.25    48.8  733.74    58.5   728.9      78  720.26
    97.5  711.98     117  704.47   136.5  697.71   146.3  694.73     156  692.56
   165.8  691.15   195.1   687.6   202.2  687.14   204.8  686.97   214.6  687.28
   217.2  687.49   253.7  690.79   282.8  693.16   292.4  694.72   302.1  697.18
   350.2   711.8   359.8  714.84   369.4  718.35     379  722.14   398.3  730.21
   407.9  734.42   417.5  738.73   436.8  747.75   484.8   770.5   513.7  783.81
#Mann= 3 , 0 , 0
       0      .1       0   202.2    .045       0   217.2      .1       0
Bank Sta=202.2,217.2
XS Rating Curve= 0 ,0
Exp/Cntr=0.3,0.1

Type RM Length L Ch R = 1 ,13603.3 ,245.7,246.2,246.4
XS GIS Cut Line= 4
     1521041.684      355000.277     1520838.559      355000.277
     1520625.018      355081.006     1520401.059      355133.089
#Sta/Elev= 30
       0  764.53    48.4  744.28    77.4  729.73      87  725.68    96.7  722.52
   116.1  717.42   164.4  706.94   174.1  704.38   183.8  701.25   203.1  693.96
   212.6  691.22   231.7   688.1   250.7  682.72   260.2  682.57   270.2  684.13
   279.2  685.85   288.7  687.14   307.8  688.23   326.8  687.38   383.9  682.82
   393.4  682.53   402.9  684.36   412.4  690.26   421.9  698.82   431.4  705.28
     441   708.5   479.3  719.25   527.2  736.95   613.4  772.29   661.4  793.72
#Mann= 3 , 0 , 0
       0     .08       0   250.7    .045       0   270.2     .08       0
#XS Ineff= 2 , 0
                          307.86           690.6
Permanent Ineff=
       F       F
Bank Sta=250.7,270.2
XS Rating Curve= 0 ,0
Exp/Cntr=0.3,0.1

Type RM Length L Ch R = 1 ,13357.1 ,439.9,432.6,425.4
XS GIS Cut Line= 4
      1521007.83      354838.818     1520710.955      354789.339
     1520572.934      354838.818     1520354.184      355028.923
#Sta/Elev= 30
       0  763.68    29.1  748.38    38.8  743.98    58.2  736.52    87.4  727.31
   135.9  716.62   155.3  711.61   174.8  705.08   203.9  693.18   213.6  690.05
   223.3  688.29   271.8  685.16   310.7  684.56   320.5  683.79   340.1  679.18
   349.8  678.82   357.7  680.49   369.4  683.32   379.2  684.11   398.7  679.09
   408.5  678.67   418.3  680.77   437.8  689.67   476.6  703.43   495.9  709.13
   553.9   724.3   582.8  733.43   592.5  737.94   689.1   787.8   737.4  809.53
#Mann= 3 , 0 , 0
       0     .08       0   340.1    .045       0   357.7     .08       0
#XS Ineff= 2 , 0
                          379.04          687.73
Permanent Ineff=
       F       F
Bank Sta=340.1,357.7
XS Rating Curve= 0 ,0
Exp/Cntr=0.3,0.1

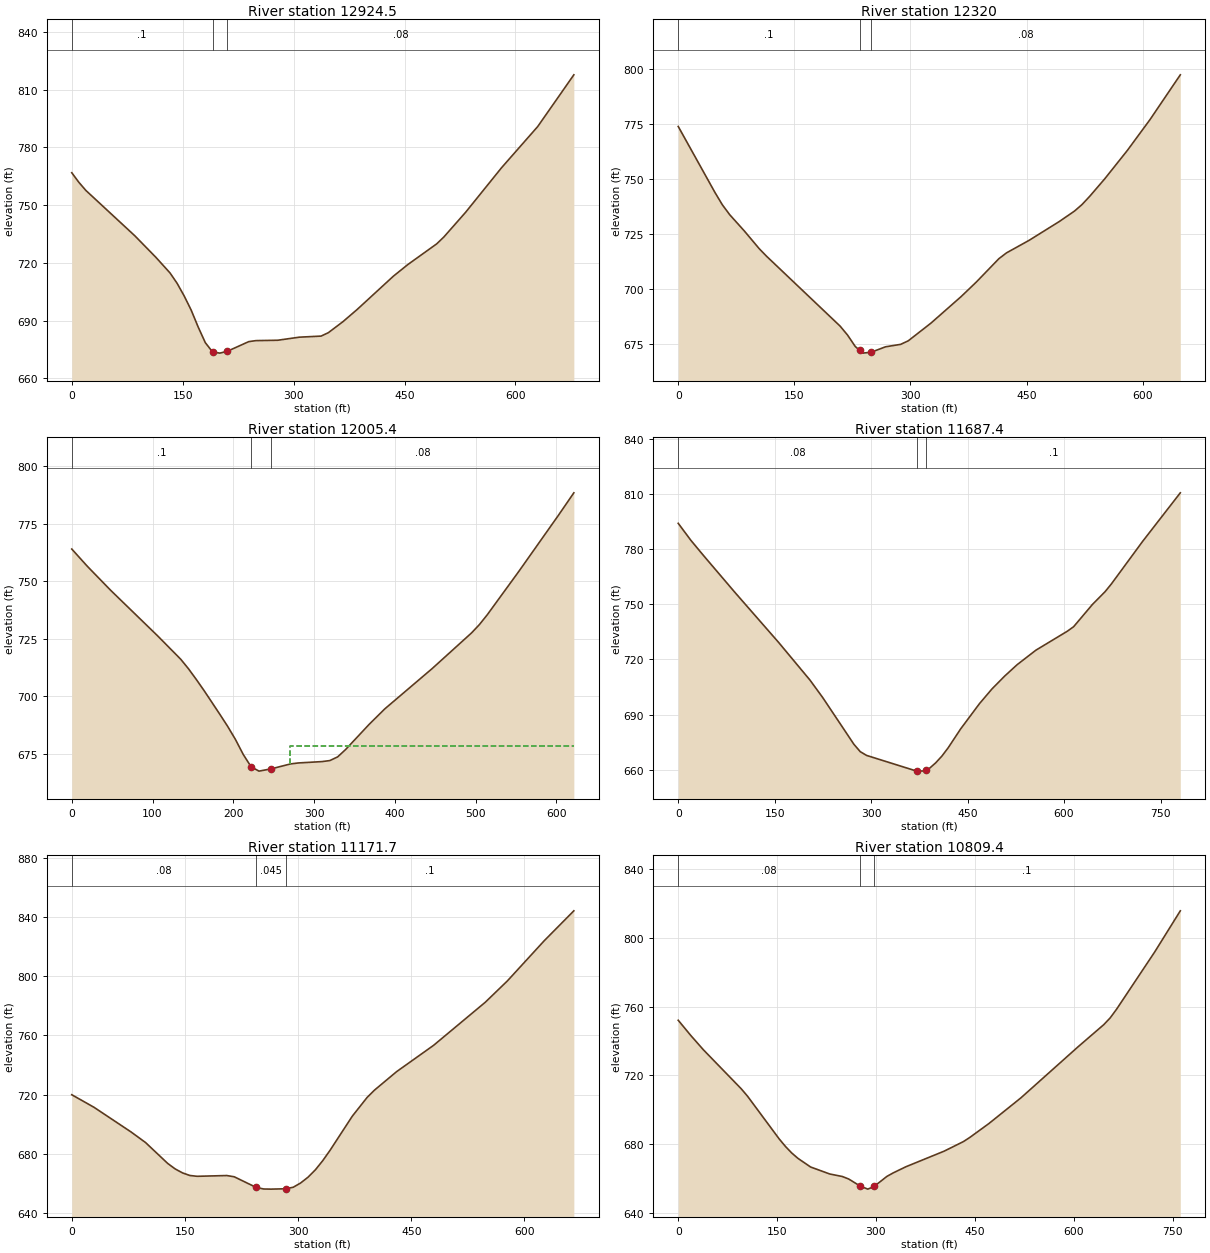
Type RM Length L Ch R = 1 ,12924.5 ,607.7,604.5,601
XS GIS Cut Line= 4
     1520640.643      354260.693     1520536.476       354396.11
     1520388.039      354508.089     1520085.955      354620.068
#Sta/Elev= 30
       0  766.88     9.5  761.96      19  757.71    85.4  734.08   113.9  722.88
   132.9  714.81   142.4  709.47   151.9  702.96   161.4  695.59   170.8  686.87
   180.6   678.6   190.4  673.78   200.2  673.16     210  674.06   239.4  679.14
   249.1  679.66   278.5  679.85   307.8  681.45   337.2  682.01     347  683.78
   366.6  689.46   386.1  695.89   434.9  713.12   454.4  719.15   493.5  729.92
   503.2  733.49   532.5  746.27   581.3  769.51   630.1  790.86     679  817.75
#Mann= 3 , 0 , 0
       0      .1       0   190.4    .045       0     210     .08       0
Bank Sta=190.4,210
XS Rating Curve= 0 ,0
Exp/Cntr=0.3,0.1

Type RM Length L Ch R = 1 ,12320   ,316.2,314.6,312.6
XS GIS Cut Line= 3
     1520360.405      353789.014     1520197.211      353903.597
     1519881.239      354223.042
#Sta/Elev= 30
       0  773.88    47.5  743.78      57   738.2    66.5  733.69    85.5  726.24
   104.4   718.3   113.9  714.84   209.2  682.92   218.9   678.8   228.7  673.66
   234.6  671.84   238.5  670.63   249.6  671.07   267.8  673.51   287.3  674.62
   297.1  676.21   326.4  684.26   365.4  696.35     385  702.96   414.3  713.65
   424.1  716.29   453.4  722.02   492.4  730.59     512  735.34   521.7  738.31
   531.5     742     551     750   580.3  762.97   609.6  777.03   648.7   797.4
#Mann= 3 , 0 , 0
       0      .1       0   234.6    .045       0   249.6     .08       0
Bank Sta=234.6,249.6
XS Rating Curve= 0 ,0
Exp/Cntr=0.3,0.1

Type RM Length L Ch R = 1 ,12005.4 ,315.4,318,320.3
XS GIS Cut Line= 3
     1520084.031      353574.253     1519939.934      353716.614
     1519670.837      354037.795
#Sta/Elev= 30
       0  764.02    19.3  756.52    48.2  746.08   106.1  726.38     135  716.12
   144.7  711.93   154.3  707.31     164  702.44   183.3  692.26   192.9  687.06
   202.6  681.35   212.3   674.8     222  669.46   231.8  667.56   246.8  668.54
   270.8  670.68   280.5  671.11   309.8   671.7   319.5  672.14   329.2  673.75
     339  676.93   368.2  687.88   387.7  694.64   446.2   712.1   494.9  727.57
   504.6  731.17   514.4  735.46   553.4  754.26   602.1  778.46   621.6  788.43
#Mann= 3 , 0 , 0
       0      .1       0     222    .045       0   246.8     .08       0
#XS Ineff= 2 , 0
                          270.68          678.67
Permanent Ineff=
       F       F
Bank Sta=222,246.8
XS Rating Curve= 0 ,0
Exp/Cntr=0.3,0.1

Type RM Length L Ch R = 1 ,11687.4 ,515.6,515.7,515.9
XS GIS Cut Line= 2
       1519898.6      353375.819     1519343.044       353924.43
#Sta/Elev= 30
       0  794.01    19.5  784.84      39  776.63    87.8  756.61   156.2  729.24
     205  708.75   224.5   699.4   273.3  673.86     283  669.92   292.8  667.87
   370.9  659.32   380.6   659.4     386  660.14   390.4  660.74   400.2  663.77
   409.9  667.43   419.7  671.95   439.2  682.26   468.5  696.01     488  704.02
   507.5  710.92     527  717.16   556.3  725.07   605.1  735.36   614.9  737.81
   644.1  749.89   663.7  756.81   673.4  760.96   722.2  784.19   780.8  810.58
#Mann= 3 , 0 , 0
       0     .08       0   370.9    .045       0     386      .1       0
Bank Sta=370.9,386
XS Rating Curve= 0 ,0
Exp/Cntr=0.3,0.1

Type RM Length L Ch R = 1 ,11171.7 ,366.4,362.3,358
XS GIS Cut Line= 2
     1519457.628      353091.097     1518985.405      353559.847
#Sta/Elev= 30
       0  719.99    29.4  711.54    78.3  694.98    97.8  687.74   127.2  673.62
     137  669.96   146.8  667.26   156.6  665.51   166.3  664.97   205.5  665.48
   215.3  664.65   244.6  657.42   254.4  656.41   264.2  656.32   283.8  656.56
   293.6  657.61   303.3  660.46   313.1  664.36   322.9  669.37   332.7  675.57
   342.5  682.66   371.8  705.53   391.4  718.15   401.2   723.1   430.5  735.56
   479.5   753.3     548  782.36   577.3  796.75   626.2  823.89   665.4  844.04
#Mann= 3 , 0 , 0
       0     .08       0   244.6    .045       0   283.8      .1       0
Bank Sta=244.6,283.8
XS Rating Curve= 0 ,0
Exp/Cntr=0.3,0.1

Type RM Length L Ch R = 1 ,10809.4 ,473.4,471.7,469.9
XS GIS Cut Line= 4
     1519110.405      352778.597     1519047.905      352969.569
     1518971.517       353080.68     1518832.628      353483.458
#Sta/Elev= 30
       0  752.09    19.1   743.2    38.3  734.84    95.7  712.13   105.2  707.83
   153.1     683   162.7  678.58   172.2  674.77   181.8   671.6   200.9   666.6
   229.8  662.55   249.1  661.06   258.7   659.6   275.8  655.57   287.6  653.72
   297.2  655.28   316.5   661.1   326.1  663.16   345.5  666.76   403.6  675.86
   432.6  681.39   442.3   683.8   471.3   691.9   519.8  706.84   606.9  736.71
   645.6  749.51   655.3  753.43     665  758.48   723.1  791.97   761.8  815.84
#Mann= 3 , 0 , 0
       0     .08       0   275.8    .045       0   297.2      .1       0
Bank Sta=275.8,297.2
XS Rating Curve= 0 ,0
Exp/Cntr=0.3,0.1

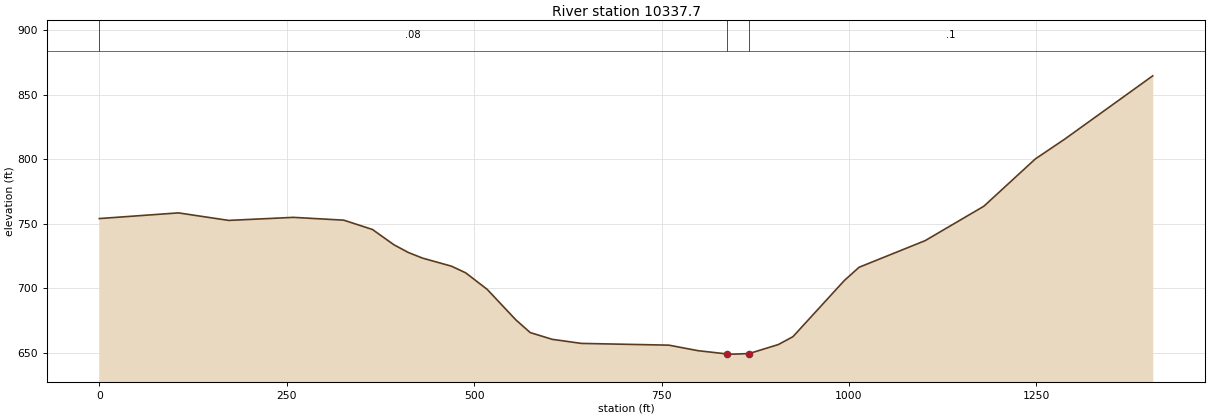
Type RM Length L Ch R = 1 ,10337.7 ,135.5,152.9,165.8
XS GIS Cut Line= 5
     1519120.822      352337.625     1518927.217      352646.253
     1518718.044      352622.347     1518547.905      352917.486
     1518464.572      353400.125
#Sta/Elev= 30
       0  754.07   105.5  758.48   172.6  752.64   258.9  755.01     326  752.84
   364.3  745.62     393  733.75   412.2  727.76   431.3  723.37   469.6  717.16
   488.7  711.99   517.4  699.16   555.7  675.46   574.9  665.61   604.1   660.4
     643  657.23   759.8  655.87   798.7  651.58   837.7  649.02   847.4  648.91
   866.9  649.37   905.8  656.33   925.3  662.44   993.9  706.04  1013.5  716.28
  1101.6  736.92    1180  763.64  1248.6   800.3  1287.8  815.66  1405.3   864.8
#Mann= 3 , 0 , 0
       0     .08       0   837.7    .045       0   866.9      .1       0
Bank Sta=837.7,866.9
XS Rating Curve= 0 ,0
Exp/Cntr=0.3,0.1