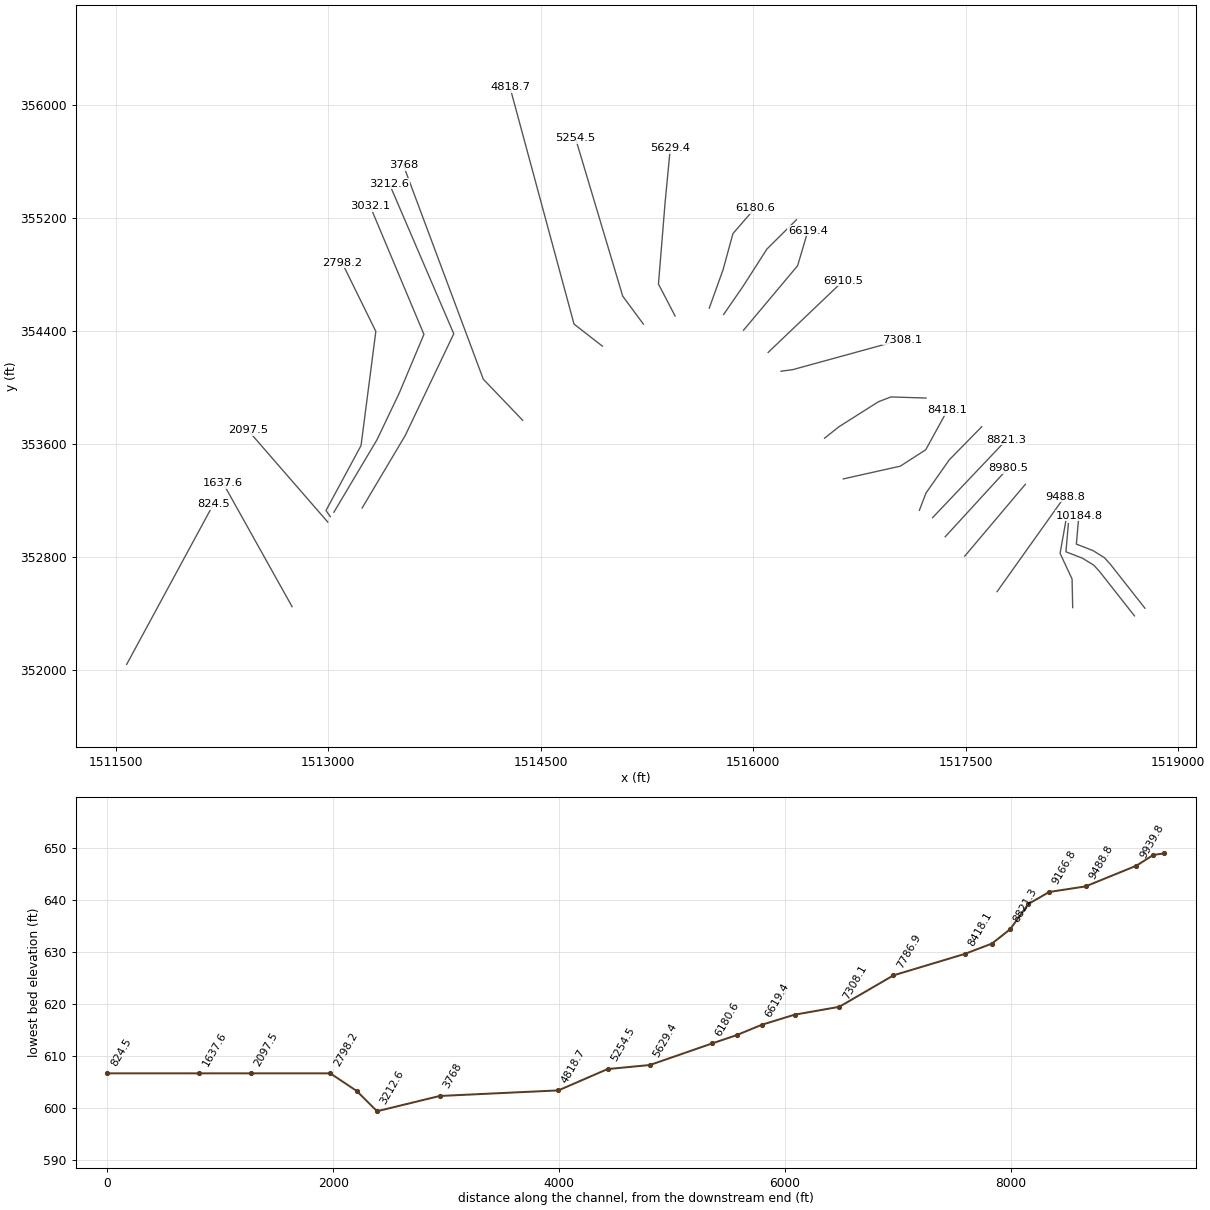
HEC-RAS study BENSRN.prj: BENSRN

--- BENSRN.g01 (geometry) --- (continued)

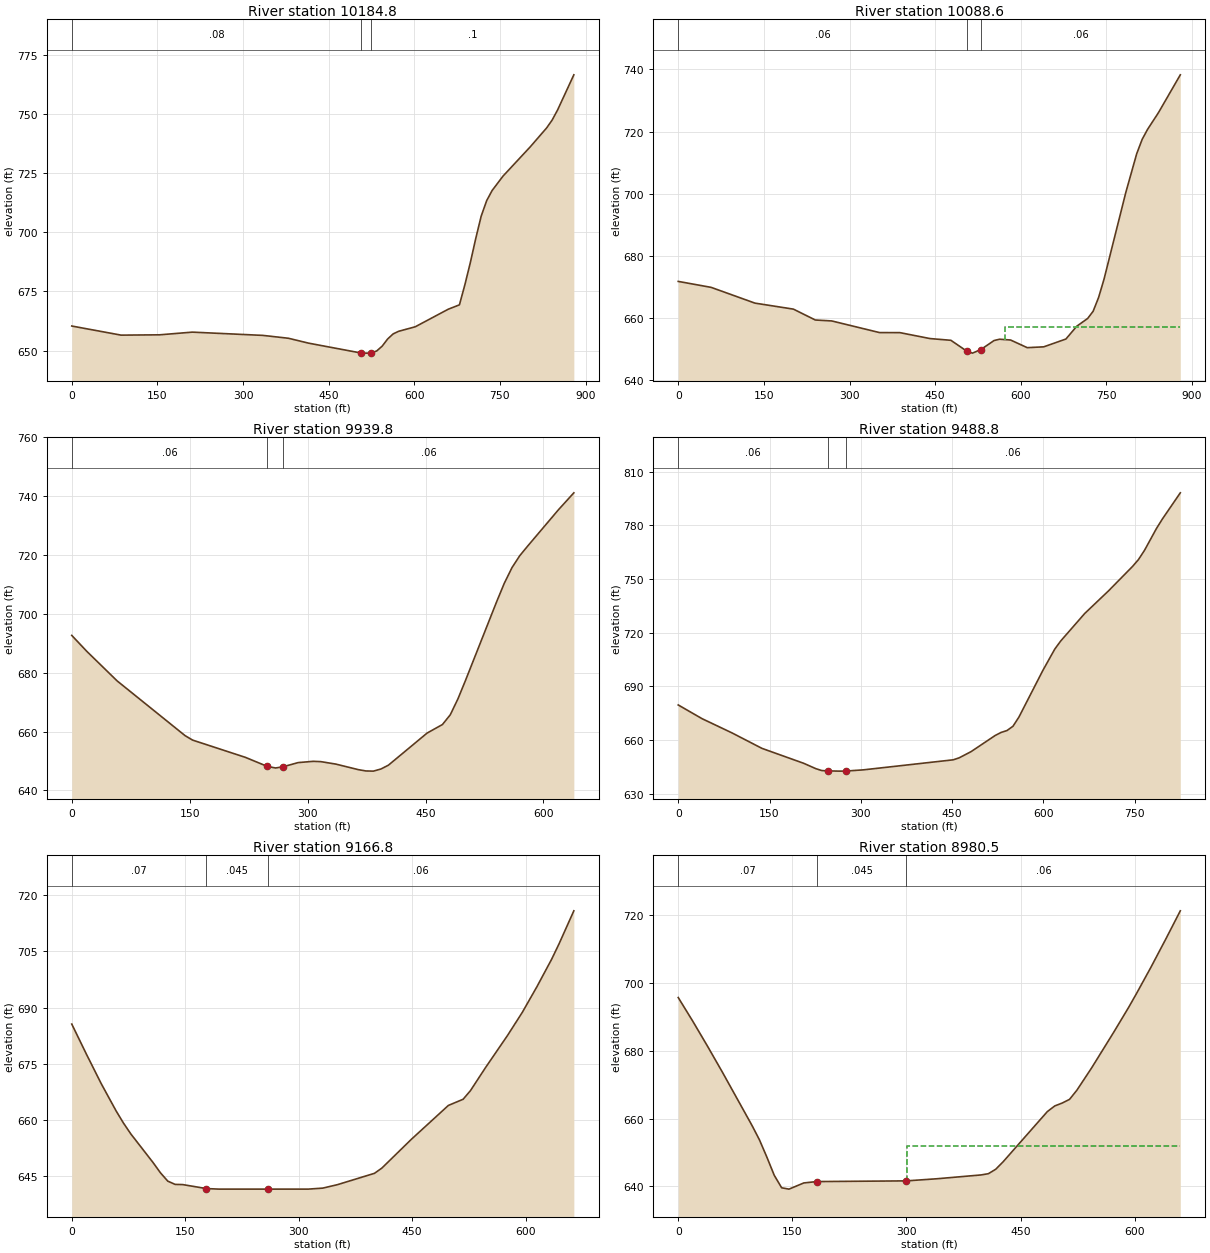
Type RM Length L Ch R = 1 ,10184.8 ,101.2,96.1,94.7
XS GIS Cut Line= 6
     1518765.209        352440.2     1518519.983        352752.7
      1518478.75      352798.273     1518398.455      352848.186
     1518281.268      352893.759     1518298.629      353093.412
#Sta/Elev= 30
       0  660.36    86.4  656.51   153.6  656.64   211.3  657.78   334.8   656.4
   379.4  655.19   414.8  653.12   506.4  648.96   515.4   648.9   524.9  648.95
   534.3  649.86   543.8  651.88   553.2  654.86   562.9  657.03   572.6  658.14
   601.6  660.04   659.6  667.49     679  669.32   688.5  677.78   698.1  687.19
   707.6   697.4   717.1  706.83   726.7  713.39   736.2  717.66   755.3  723.76
     803  736.14   831.7  744.14   841.2   747.4   850.8  751.68   879.4  766.61
#Mann= 3 , 0 , 0
       0     .08       0   506.4    .045       0   524.9      .1       0
Bank Sta=506.4,524.9
XS Rating Curve= 0 ,0
Exp/Cntr=0.3,0.1

Type RM Length L Ch R = 1 ,10088.6 ,163.4,148.8,134.8
XS GIS Cut Line= 6
     1518691.424      352385.947     1518446.198      352698.447
     1518404.966       352744.02      1518324.67      352793.933
     1518207.483      352839.506     1518224.844      353039.158
#Sta/Elev= 30
       0  671.72    57.6   669.8   134.4  664.72   201.7  662.79   240.1  659.28
   268.9  658.98   352.6  655.23   388.3  655.21   441.1   653.3   477.6  652.74
     506  649.17   515.4  648.61   530.1  649.77   553.2  652.67   562.9  653.09
   582.2  652.83   611.3  650.37   640.3  650.64     679  653.15   698.1  657.29
   717.1  659.77   726.7   662.1   736.2   666.5   745.8  672.44     784  700.42
     803  712.84   812.6   717.5   822.1  720.72   841.2  726.11   879.4  738.28
#Mann= 3 , 0 , 0
       0     .06       0     506    .045       0   530.1     .06       0
#XS Ineff= 2 , 0
                          572.24          657.17
Permanent Ineff=
       F       F
Bank Sta=506,530.1
XS Rating Curve= 0 ,0
Exp/Cntr=0.3,0.1

Type RM Length L Ch R = 1 ,9939.8  ,474.3,451,427.3
XS GIS Cut Line= 4
     1518255.226       352444.54     1518250.886      352646.363
      1518166.25      352828.655     1518207.483       353060.86
#Sta/Elev= 30
       0  692.68    19.2  687.25    57.7  677.22   144.2   658.6   153.8  657.09
     221  651.22   248.9  648.14   259.3  647.62   268.9  648.04     288  649.45
   307.2  649.88   316.7  649.78   335.9  648.94   364.6  647.05   374.1  646.61
   383.7  646.55   393.3  647.27   402.8  648.57     452  659.48   471.6   662.4
   481.5   665.7   491.3  671.14   501.1  677.53   540.4  704.07   550.2  710.39
   560.1  715.76   569.9  719.78   579.7  722.96     619  735.36   638.7  741.15
#Mann= 3 , 0 , 0
       0     .06       0   248.9    .045       0   268.9     .06       0
Bank Sta=248.9,268.9
XS Rating Curve= 0 ,0
Exp/Cntr=0.3,0.1

Type RM Length L Ch R = 1 ,9488.8  ,323.2,322,320.3
XS GIS Cut Line= 2
     1517721.372      352557.388     1518198.802      353230.131
#Sta/Elev= 30
       0  679.56    39.3  671.86    88.4  663.93   137.5   655.3   206.2  646.94
   225.9  643.97   235.7  642.89   245.5  642.71   265.2  642.57     275   642.6
   304.4  643.29   451.8  648.89   461.6     650   481.2  653.48   520.5  662.44
   530.3  664.18   540.1  665.25     550  667.66   559.8  672.82   599.1  698.88
   618.7  710.81   628.5  715.36   667.8  730.67   707.1  743.39   746.4  756.99
   756.2  760.86     766  765.95   785.7   778.2   795.5  783.54   824.9  798.14
#Mann= 3 , 0 , 0
       0     .06       0   245.5    .045       0     275     .06       0
Bank Sta=245.5,275
XS Rating Curve= 0 ,0
Exp/Cntr=0.3,0.1

Type RM Length L Ch R = 1 ,9166.8  ,187.2,186.3,185.3
XS GIS Cut Line= 2
     1517493.507      352809.124     1517921.025      353316.936
#Sta/Elev= 30
       0  685.58    19.5  677.49      39  669.65    58.6   662.4    68.3  659.16
    78.1  656.24   107.4  648.62   117.1   645.9   126.9  643.64   136.7  642.76
   146.4  642.72     178641.6472   195.2   641.5     260   641.5   312.4   641.5
   331.9  641.77   351.4   642.7   400.2  645.72     410  647.12     449  654.81
   497.9  663.85   517.4   665.5   527.1   667.8   546.7  673.86     576  682.51
   595.5  688.66     615  695.57   634.5  702.92   644.3  707.04   663.8  715.83
#Mann= 3 , 0 , 0
       0     .07       0     178    .045       0     260     .06       0
Bank Sta=178,260
XS Rating Curve= 0 ,0
Exp/Cntr=0.3,0.1

Type RM Length L Ch R = 1 ,8980.5  ,159.6,159.2,158.8
XS GIS Cut Line= 2
     1517355.197      352945.897      1517800.51      353432.876
#Sta/Elev= 30
       0  695.68    19.4  688.59    38.8  681.21    58.2  673.61      97  657.94
   106.8  653.69   116.4  648.67   126.2  643.26   135.9  639.58   145.6  639.18
     165     641     182641.4078     300641.6134   339.6  642.23   397.9  643.36
   407.6  643.73   417.3  645.04     427  647.24   485.2  662.06   494.9  663.71
   504.6  664.56   514.3  665.65     524  668.36   543.4  674.95   572.6  685.53
     592  692.78   601.7  696.61   621.1  704.53   640.5  712.79   659.9  721.25
#Mann= 3 , 0 , 0
       0     .07       0     182    .045       0     300     .06       0
#XS Ineff= 2 , 0
                          300.92           651.8
Permanent Ineff=
       F       F
Bank Sta=182,300
XS Rating Curve= 0 ,0
Exp/Cntr=0.3,0.1

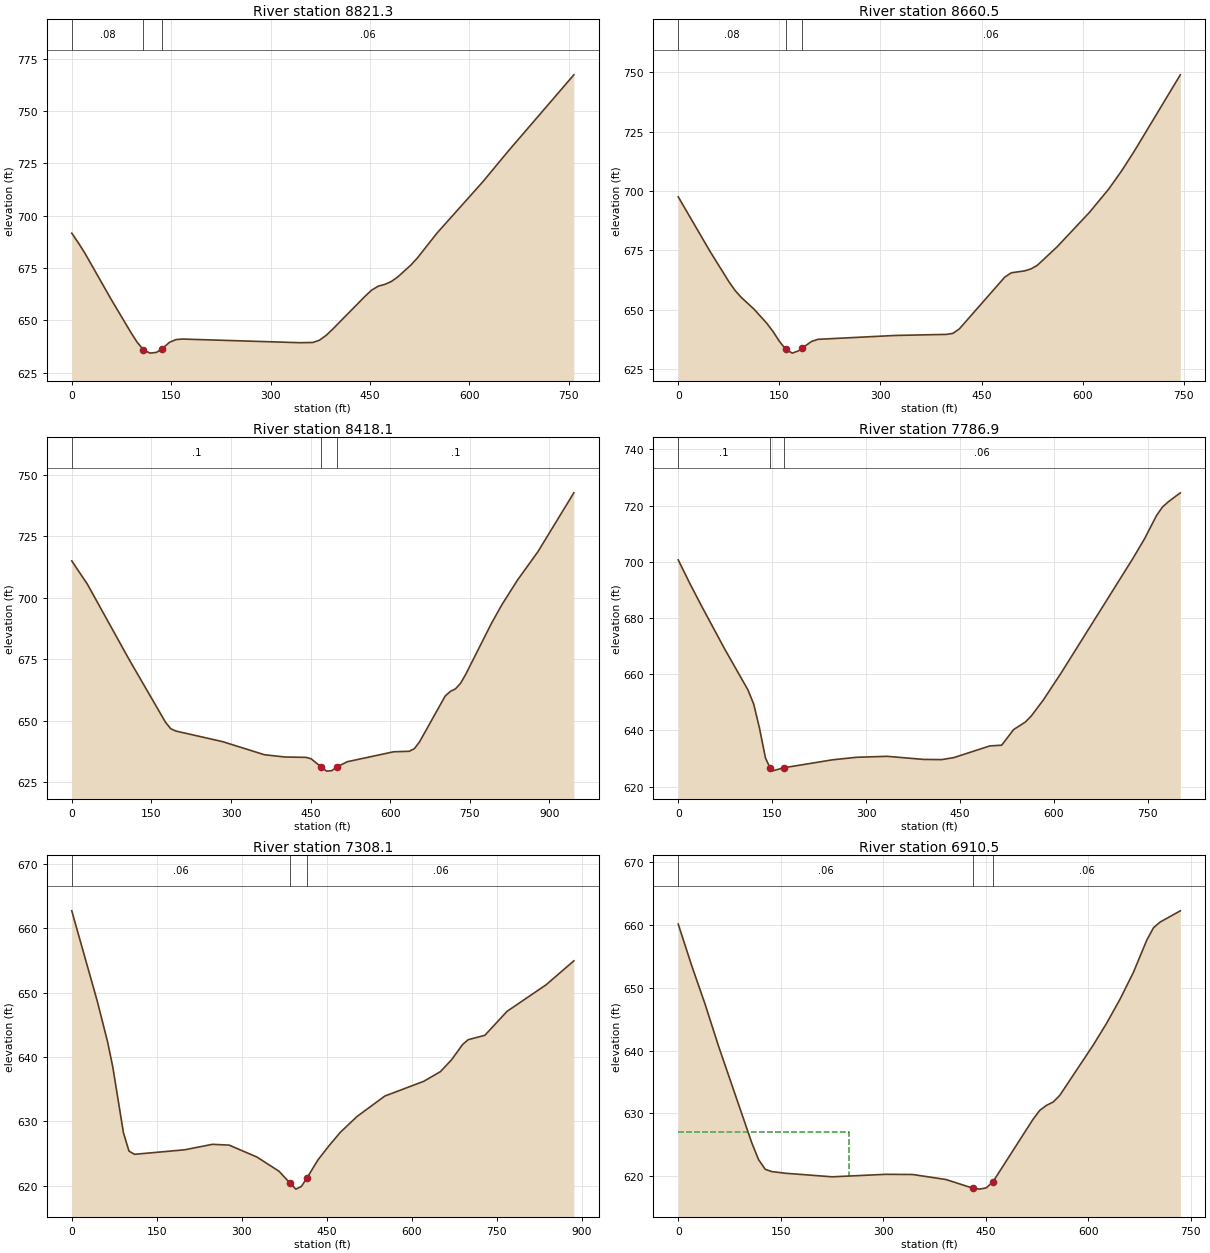
Type RM Length L Ch R = 1 ,8821.3  ,157.3,160.9,164.1
XS GIS Cut Line= 2
     1517266.323      353081.198     1517787.156      353631.545
#Sta/Elev= 30
       0  691.64     9.8   687.1    19.7  682.17      59  660.29    88.6  644.56
    98.4  639.69   108.2  635.92   118.1  634.36   127.9  634.72   135.8  636.31
   147.6  639.56   157.4  640.84   167.3  641.08   344.4  639.34   364.1  639.45
   373.9  640.56   383.8  642.82   393.6  645.74   442.8  661.58   452.7  664.47
   462.5  666.34   472.4  667.19   482.2  668.56     492  670.75   511.7   676.4
   521.6  679.82   551.1  691.66     620  716.08   659.3  731.06   757.7  767.28
#Mann= 3 , 0 , 0
       0     .08       0   108.2    .045       0   135.8     .06       0
Bank Sta=108.2,135.8
XS Rating Curve= 0 ,0
Exp/Cntr=0.3,0.1

Type RM Length L Ch R = 1 ,8660.5  ,251.3,242.4,233.7
XS GIS Cut Line= 4
     1517172.905      353133.397      1517219.78      353255.793
     1517383.843      353490.168      1517613.01      353724.543
#Sta/Elev= 30
       0  697.51    46.8   674.7    74.9  661.86    84.3  658.06    93.6  655.09
   112.3   650.2   131.1  644.31   140.6  640.76   150.1  636.58   159.7  633.19
   169.2  631.61   178.8  632.62   183.3   633.6   197.8  636.54   207.4  637.43
   321.8  639.06   398.1  639.51   407.6  639.94   417.2  641.85   484.6  663.69
   494.3  665.49   513.6  666.28   523.2   667.1   532.8  668.64   561.8  676.32
     610  690.91   638.9  700.84   658.2  708.58   677.5  717.14     745  748.97
#Mann= 3 , 0 , 0
       0     .08       0   159.7    .045       0   183.3     .06       0
Bank Sta=159.7,183.3
XS Rating Curve= 0 ,0
Exp/Cntr=0.3,0.1

Type RM Length L Ch R = 1 ,8418.1  ,631.3,631.2,630.8
XS GIS Cut Line= 4
     1516636.138      353355.564     1517038.143       353445.52
     1517217.919      353561.819     1517371.527      353842.511
#Sta/Elev= 30
       0  714.94    29.4   705.5   107.9  674.99   176.6  649.46   186.4  646.84
   196.2  645.88   284.4  641.57   362.9  636.27   402.1  635.33   441.1   635.2
   450.9  634.63   470.3  631.24   480.1  629.61   489.8  629.79   499.5  631.28
     519  633.42   606.6  637.47   635.8  637.66   645.4   638.7   655.2  641.46
   703.6   660.1   713.3  661.97     723  663.02   732.7  665.31   742.4  668.95
   790.9  689.64   810.3  697.11   839.4  707.03   878.2  718.64     946  742.58
#Mann= 3 , 0 , 0
       0      .1       0   470.3    .045       0   499.5      .1       0
Bank Sta=470.3,499.5
XS Rating Curve= 0 ,0
Exp/Cntr=0.3,0.1

Type RM Length L Ch R = 1 ,7786.9  ,485.6,478.9,471.9
XS GIS Cut Line= 5
     1516503.635      353643.813     1516605.197      353724.543
     1516883.843      353901.626     1516972.385       353935.48
      1517219.78      353927.668
#Sta/Elev= 30
       0   700.7    18.5  692.32    37.1  684.34    74.1  669.02   111.2  654.49
   120.5  649.43   129.7  640.92   139.4  630.17  147.03626.5341   149.2   625.5
   168.6  626.69   246.3  629.52   285.1  630.43   333.7  630.77   391.9  629.67
     421   629.6   440.5  630.32   497.8  634.47   516.8  634.73   535.7  640.26
   554.7  642.99   564.2  645.16   583.2  650.78   611.8  660.44     726  701.04
   745.1  708.22   764.1  716.45   773.6  719.48   783.2   721.4   802.2  724.56
#Mann= 3 , 0 , 0
       0      .1       0  147.03    .045       0   168.6     .06       0
Bank Sta=147.03,168.6
XS Rating Curve= 0 ,0
Exp/Cntr=0.3,0.1

Type RM Length L Ch R = 1 ,7308.1  ,386.6,397.6,408.6
XS GIS Cut Line= 3
     1516196.343      354117.772     1516277.072      354128.188
     1517053.114       354341.73
#Sta/Elev= 30
       0  662.71    45.2  648.62    63.3  642.33    72.4  638.46    91.2  628.24
     101  625.38   110.8  624.88   199.2  625.58   248.3  626.43   277.7  626.31
   326.8  624.46     366  622.24   385.7  620.36   395.5  619.47   405.3  619.88
   415.1  621.19   434.8  624.04   454.4  626.24     474  628.29   503.5  630.75
   552.6  633.93   621.3  636.22   650.7  637.72   670.3  639.55     690  641.95
   699.8  642.69   729.2  643.37   768.5   647.1   837.2  651.21   886.3  654.94
#Mann= 3 , 0 , 0
       0     .06       0   385.7    .045       0   415.1     .06       0
Bank Sta=385.7,415.1
XS Rating Curve= 0 ,0
Exp/Cntr=0.3,0.1

Type RM Length L Ch R = 1 ,6910.5  ,288.3,291,293.8
XS GIS Cut Line= 2
     1516105.197      354250.584     1516636.447      354758.397
#Sta/Elev= 30
       0  660.17    19.6  653.59    39.2  647.45    58.8   640.8   107.8  625.28
   117.6  622.65   127.4   621.1   137.2  620.74   156.8  620.48   225.4  619.91
   303.8  620.31     343  620.28     392  619.48   431.2   618.1     441  617.95
   450.8  618.15   460.6  619.11   519.3  629.07   529.1  630.49   538.9  631.29
   548.7  631.82   558.5  632.89   607.5  640.91   627.1  644.39   646.7  648.22
   666.3   652.5   685.9  657.64   695.7   659.6   705.5  660.51   734.9  662.29
#Mann= 3 , 0 , 0
       0     .06       0   431.2    .045       0   460.6     .06       0
#XS Ineff= 2 , 0
          250.42   627.1
Permanent Ineff=
       F       F
Bank Sta=431.2,460.6
XS Rating Curve= 0 ,0
Exp/Cntr=0.3,0.1

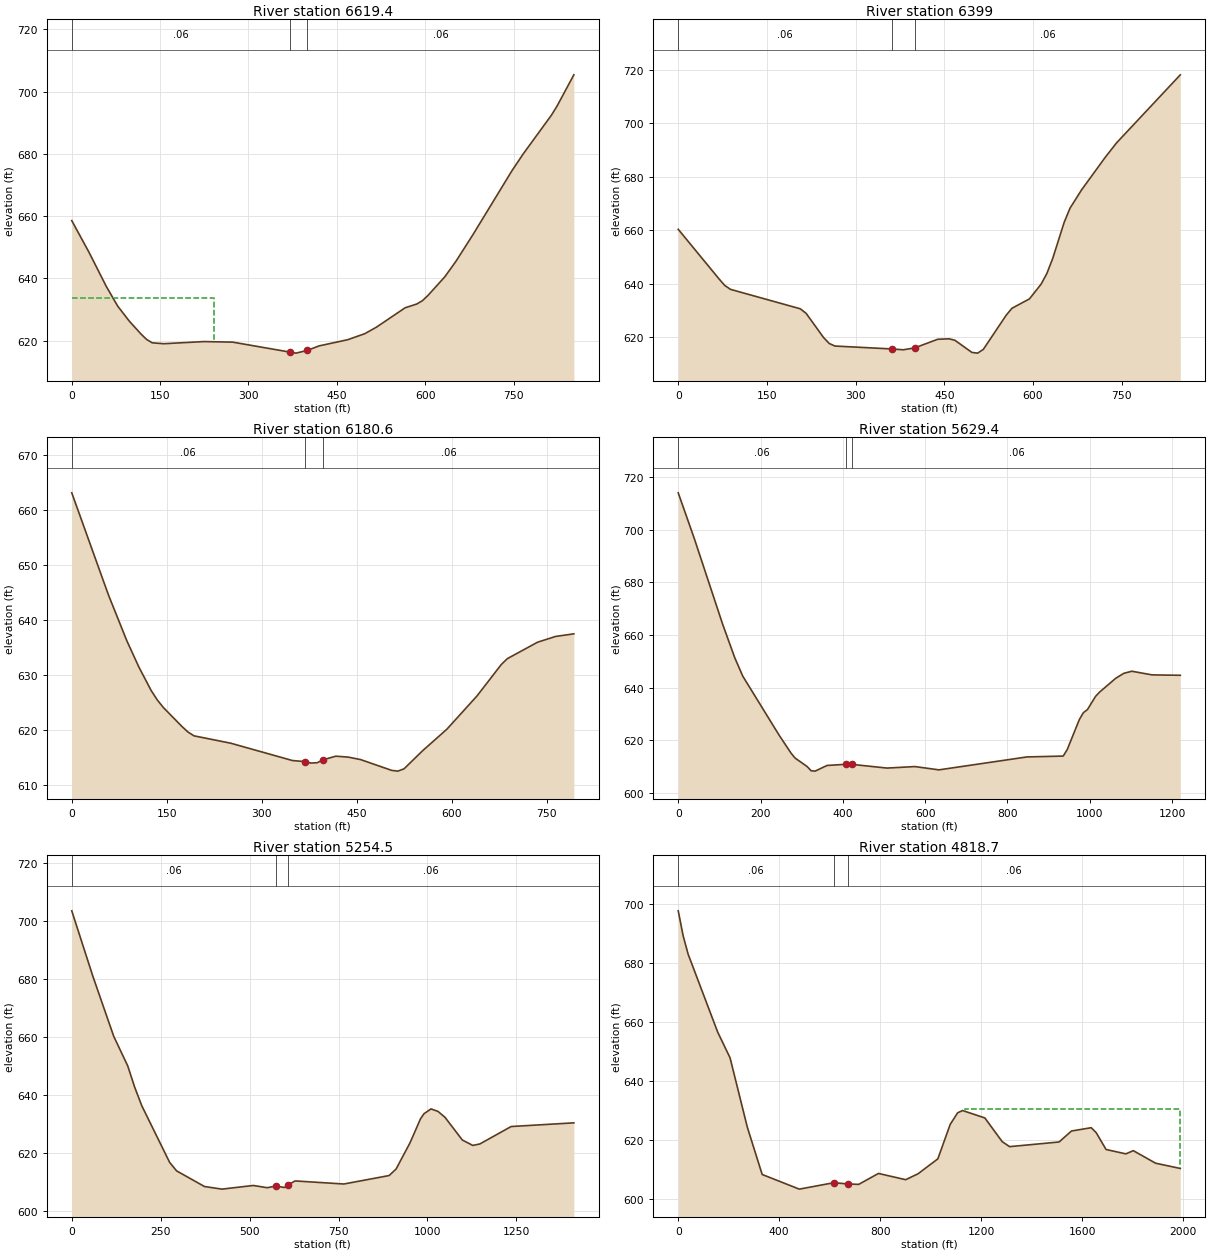
Type RM Length L Ch R = 1 ,6619.4  ,217.4,220.4,223.2
XS GIS Cut Line= 3
     1515931.253      354407.586     1516313.198      354864.184
     1516386.114      355110.711
#Sta/Elev= 30
       0  658.55    29.3  648.38    58.6  637.43    78.1  631.07    97.6   626.3
   117.1  622.23   126.9  620.43   136.6  619.32   156.1  619.03   224.4  619.72
   273.2  619.54   370.7  616.33   380.6  616.01   400.1  616.89   419.6  618.32
   468.4  620.31   497.7  622.27   517.2  624.34     566  630.57   585.5  631.76
   595.3  632.84   604.8  634.55   633.4  640.52   652.4  645.54     681  654.01
   747.6  674.66   766.7  680.04   814.3  692.39   823.8   695.3   852.4  705.36
#Mann= 3 , 0 , 0
       0     .06       0   370.7    .045       0   400.1     .06       0
#XS Ineff= 2 , 0
           241.5   633.6
Permanent Ineff=
       F       F
Bank Sta=370.7,400.1
XS Rating Curve= 0 ,0
Exp/Cntr=0.3,0.1

Type RM Length L Ch R = 1 ,6399    ,211.7,218.4,225.2
XS GIS Cut Line= 4
     1515790.866       354518.94     1515929.975      354721.439
     1516096.196      354981.737     1516304.845      355189.565
#Sta/Elev= 30
       0  660.36    68.8  641.85    78.6  639.37    88.4  637.89   206.4  630.62
   216.2  628.94   245.7  619.89   255.3  617.65     265  616.69   361.5   615.6
   380.8  615.29   400.1  616.02   438.7  619.22     458  619.39   467.7  618.87
   496.6   614.3   506.3  614.04   515.9  615.44   554.5   628.2   564.3  630.82
   593.8  634.31   613.4  639.77   623.2  643.76     633   649.3   652.7  663.01
   662.5  668.26   682.1  675.12   721.4  687.09     741  692.64     849  718.14
#Mann= 3 , 0 , 0
       0     .06       0   361.5    .045       0   400.1     .06       0
Bank Sta=361.5,400.1
XS Rating Curve= 0 ,0
Exp/Cntr=0.3,0.1

Type RM Length L Ch R = 1 ,6180.6  ,549.3,551.2,549.5
XS GIS Cut Line= 4
     1515689.394      354563.697     1515787.156      354836.406
       1515856.6      355091.614      1516012.85       355272.17
#Sta/Elev= 30
       0  663.08    57.9  644.51    86.9  636.18   106.2  631.33   125.5  627.09
   135.2  625.37   144.8     624   173.8  620.59   183.5  619.56   193.1  618.86
   251.1  617.52   348.5  614.37   368.1  614.17   377.9  613.91   387.7  613.97
   397.5  614.52     417  615.16   436.6  614.99   456.2  614.54   505.2  612.58
     515  612.44   524.8  612.86   554.2  616.16   592.4  620.06   640.2  626.14
   678.4  631.84   687.9   632.9   735.7   635.9   764.3  636.95     793  637.42
#Mann= 3 , 0 , 0
       0     .06       0   368.1    .045       0   397.5     .06       0
Bank Sta=368.1,397.5
XS Rating Curve= 0 ,0
Exp/Cntr=0.3,0.1

Type RM Length L Ch R = 1 ,5629.4  ,363.5,374.9,386.2
XS GIS Cut Line= 4
     1515448.296      354508.397     1515330.806      354734.515
     1515378.028      355315.071     1515414.442      355695.897
#Sta/Elev= 30
       0  714.02    39.2  696.58   107.8  664.16   137.2  651.44   156.8  644.38
     245  621.99   274.2  615.11   283.9  613.27   313.1  610.05   322.8  608.45
   332.5   608.3   361.6  610.45   408.2   610.9   423.2  610.84   507.2  609.46
   575.2  610.03   633.4  608.78   847.1  613.69   935.4  614.02   945.2  616.51
   974.6   627.9   984.4  630.51   994.2  631.67  1013.9  636.68  1023.7  638.31
  1062.9  643.56  1082.5  645.44  1102.1  646.25  1151.2  644.86  1219.9  644.71
#Mann= 3 , 0 , 0
       0     .06       0   408.2    .045       0   423.2     .06       0
Bank Sta=408.2,423.2
XS Rating Curve= 0 ,0
Exp/Cntr=0.3,0.1

Type RM Length L Ch R = 1 ,5254.5  ,471.3,435.8,428.2
XS GIS Cut Line= 3
     1515224.338      354451.105     1515078.504      354649.022
     1514745.171      355766.209
#Sta/Elev= 30
       0  703.59      59  681.12     118  660.27   157.3  650.08     177  642.68
   196.7  636.34   275.2  616.75   294.8  613.82   373.2  608.42   422.2  607.52
   510.4  608.78   549.6  608.01   573.2  608.57   598.5  608.09   608.3  608.98
   627.9  610.35   765.1  609.29   892.4  612.21     912  614.48   951.2  623.54
   980.6  631.81   990.4  633.55    1010  635.21  1029.6  634.36  1049.2  632.35
  1098.2  624.47  1127.6  622.61  1147.2   623.1  1235.4  629.13  1411.7   630.4
#Mann= 3 , 0 , 0
       0     .06       0   573.2    .045       0   608.3     .06       0
Bank Sta=573.2,608.3
XS Rating Curve= 0 ,0
Exp/Cntr=0.3,0.1

Type RM Length L Ch R = 1 ,4818.7  ,1017.7,1050.7,1052.6
XS GIS Cut Line= 3
     1514935.275      354294.855     1514734.754      354451.105
     1514282.816      356126.336
#Sta/Elev= 30
       0  697.83    19.6  689.32    39.1  683.15   156.4  656.68   205.3  647.98
   273.8  624.42   332.6   608.4   479.7  603.43   616.9  605.61   672.3  605.18
     715  605.04   793.4  608.75   901.2  606.63   950.2  608.64  1028.6   613.7
  1077.7  625.41  1107.1  629.32  1126.7  630.09  1214.9  627.58  1283.5  619.54
  1312.9  617.84    1509  619.42    1558  623.14  1636.4  624.27    1656  622.58
  1695.2  616.87  1773.7  615.39  1803.1  616.48  1891.3  612.23  1989.3  610.44
#Mann= 3 , 0 , 0
       0     .06       0   616.9    .045       0   672.3     .06       0
#XS Ineff= 2 , 0
                         1135.52          630.74
Permanent Ineff=
       F       F
Bank Sta=616.9,672.3
XS Rating Curve= 0 ,0
Exp/Cntr=0.3,0.1

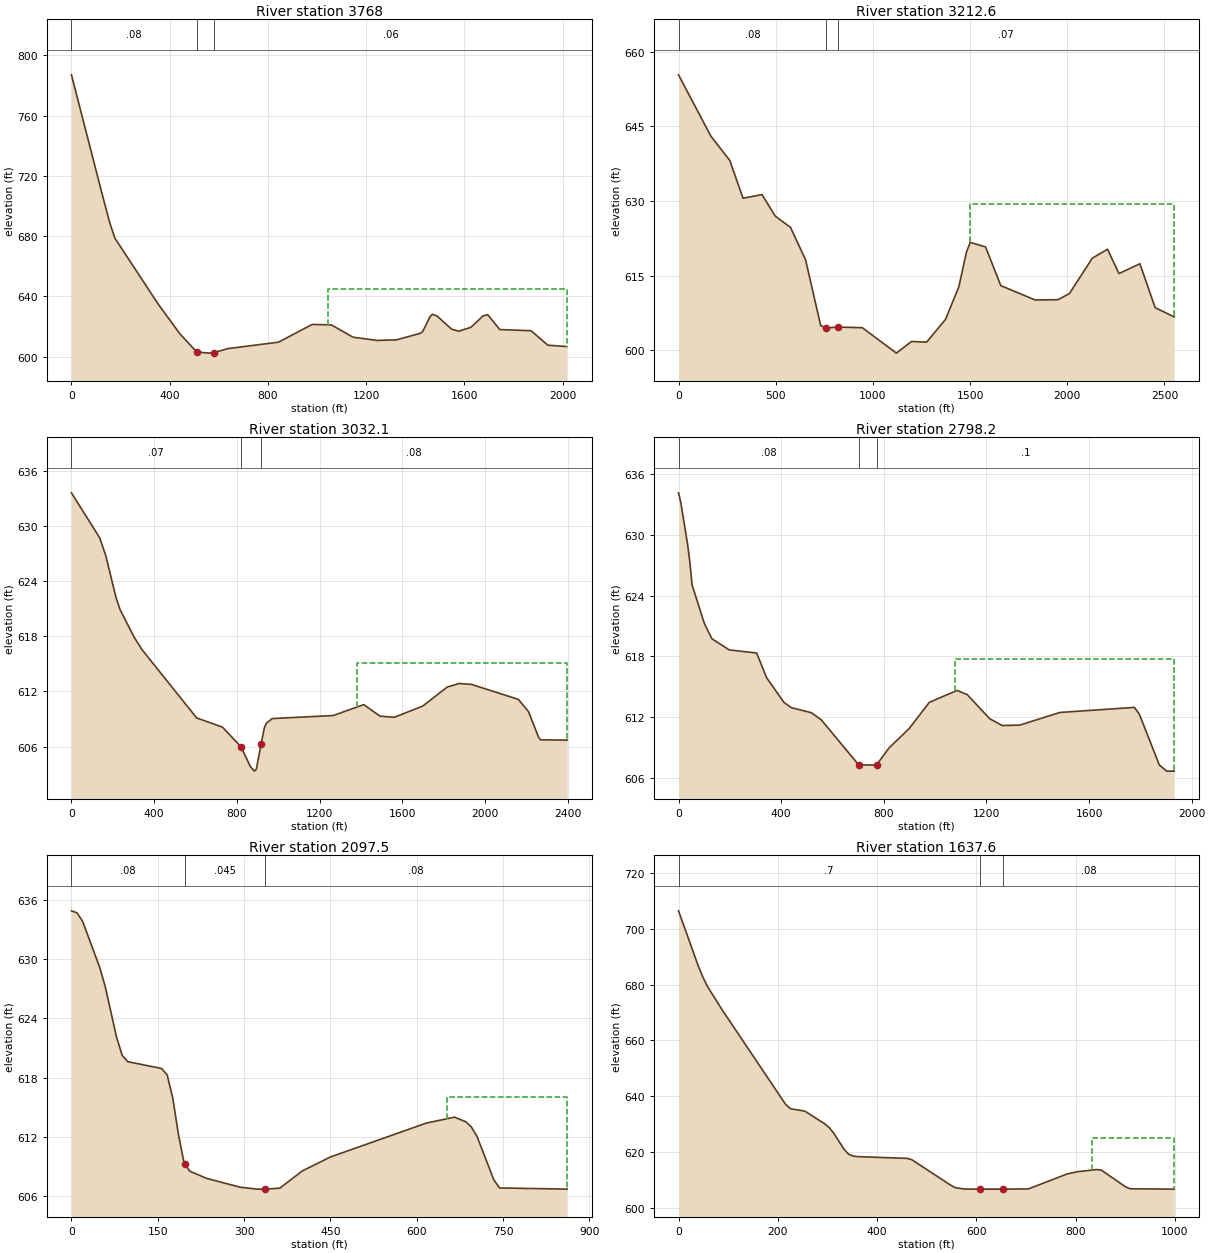
Type RM Length L Ch R = 1 ,3768    ,580.3,555.5,523.2
XS GIS Cut Line= 3
     1514371.907      353770.549     1514094.129      354061.348
     1513529.893      355576.105
#Sta/Elev= 30
       0  787.11   127.5  706.37   156.9  688.47   176.6  678.75   353.1  634.93
   441.3  615.28   509.9  603.16   558.9  602.36   578.5  602.68   637.3  605.36
     843  609.63   980.2  621.39  1058.5  621.11  1146.7  612.93  1244.6  610.79
    1323  611.16    1421  615.53  1430.8  616.81  1460.2  626.57    1470   628.2
  1489.6  626.88  1548.4  618.23  1577.7  616.94  1626.7   619.5  1675.7  627.02
  1695.3  627.87  1744.3     618  1871.6  617.25  1940.2  607.63  2018.6   606.7
#Mann= 3 , 0 , 0
       0     .08       0   509.9    .045       0   578.5     .06       0
#XS Ineff= 2 , 0
                         1045.17          644.64
Permanent Ineff=
       F       F
Bank Sta=509.9,578.5
XS Rating Curve= 0 ,0
Exp/Cntr=0.3,0.1

Type RM Length L Ch R = 1 ,3212.6  ,174.6,180.4,193.6
XS GIS Cut Line= 4
     1513239.095       353149.89     1513542.914      353662.043
     1513885.796      354382.529     1513430.067      355445.897
#Sta/Elev= 30
       0  655.32     166  643.04   263.6  638.14   331.9  630.54   429.5  631.27
   497.9  626.93     576   624.7   653.9  618.15   731.7  604.94   760.9   604.5
   819.3  604.67   945.8  604.53  1120.9  599.43  1198.8  601.77  1276.6  601.64
  1373.9  606.22  1442.4  612.78  1481.6  619.76  1501.2  621.66  1579.7  620.76
  1658.1  612.99  1834.6  610.11  1952.2  610.16  2011.1  611.39  2128.7  618.49
  2207.2   620.3    2266  615.41  2373.8  617.38  2452.3  608.56  2550.3   606.7
#Mann= 3 , 0 , 0
       0     .08       0   760.9    .045       0   819.3     .07       0
#XS Ineff= 2 , 0
                         1501.33          629.29
Permanent Ineff=
       F       F
Bank Sta=760.9,819.3
XS Rating Curve= 0 ,0
Exp/Cntr=0.3,0.1

Type RM Length L Ch R = 1 ,3032.1  ,229.5,233.9,238.4
XS GIS Cut Line= 5
     1513039.442      353119.508     1513343.261      353631.661
     1513500.357       353961.76     1513675.145       354378.42
     1513295.518      355285.306
#Sta/Elev= 30
       0  633.65   136.7  628.74     166  626.79   214.8   622.3   234.3  620.96
   302.6  617.93   341.7  616.54   605.1  609.12   730.2  608.11   819.3605.9798
   864.9  603.82   884.1  603.32   893.7  603.53   916.6 606.255   932.2  608.03
   941.8  608.53   970.9  609.05  1265.6  609.38  1412.9  610.57  1491.6  609.31
  1560.4  609.19    1698  610.41    1816  612.48    1875  612.87    1934  612.77
  2160.1  611.14  2209.2  609.81  2258.4  606.99  2268.2  606.73    2396   606.7
#Mann= 3 , 0 , 0
       0     .07       0   819.3    .045       0   916.6     .08       0
#XS Ineff= 2 , 0
                         1379.54          615.09
Permanent Ineff=
       F       F
Bank Sta=819.3,916.6
XS Rating Curve= 0 ,0
Exp/Cntr=0.3,0.1

Type RM Length L Ch R = 1 ,2798.2  ,677.6,700.7,723.6
XS GIS Cut Line= 5
     1513014.124      353088.041     1512983.742      353131.444
     1513231.137      353591.513      1513335.61      354399.008
     1513097.052      354885.885
#Sta/Elev= 30
       0  634.12     8.8  633.19    35.3  629.06    44.2  627.29      53  625.04
   101.4   621.2   130.4  619.74   198.1  618.64   304.5  618.34   343.2  615.91
   410.9  613.47   439.9  612.95   517.3  612.46     556  611.76   702.9   607.3
   771.6  607.31   820.6  608.99   899.1   610.9   977.6  613.48  1085.5  614.65
  1124.7  614.25    1213  611.86    1262  611.19  1330.7  611.24  1486.4  612.48
  1776.8  612.98  1796.2   612.3  1873.7  607.31  1902.7   606.7  1931.8   606.7
#Mann= 3 , 0 , 0
       0     .08       0   702.9    .045       0   771.6      .1       0
#XS Ineff= 2 , 0
                         1078.83          617.78
Permanent Ineff=
       F       F
Bank Sta=702.9,771.6
XS Rating Curve= 0 ,0
Exp/Cntr=0.3,0.1

Type RM Length L Ch R = 1 ,2097.5  ,464.3,459.9,455
XS GIS Cut Line= 2
     1512996.039      353050.063     1512431.803      353701.105
#Sta/Elev= 30
       0  634.89     9.8  634.68    19.6   633.8      49  629.18    58.7  627.22
    78.3  622.11    88.1  620.26    97.9  619.61   156.6  618.92   166.4  618.27
   176.2  615.89     186  612.23   195.8  609.34     197609.2396   205.6  608.52
     235  607.79   293.7  606.89   323.1   606.7     336   606.7   362.2   606.8
   401.4  608.55   450.3  609.96   616.8  613.39   665.7  613.99   685.3  613.53
   695.1  612.99   704.9  612.03   734.2  607.63     744  606.82   861.5   606.7
#Mann= 3 , 0 , 0
       0     .08       0     197    .045       0     336     .08       0
#XS Ineff= 2 , 0
                          652.79          616.06
Permanent Ineff=
       F       F
Bank Sta=197,336
XS Rating Curve= 0 ,0
Exp/Cntr=0.3,0.1

Type RM Length L Ch R = 1 ,1637.6  ,836.9,813.1,787
XS GIS Cut Line= 2
     1512744.303      352451.105     1512258.192      353323.501
#Sta/Elev= 30
       0  706.44    39.2  686.98      49  682.72    58.8   679.2    88.1   670.9
   215.4  637.17   225.2  635.53   254.6  634.65   293.7  630.21   303.5  628.81
   313.3  626.63   332.9  621.13   342.7  619.21   352.5  618.52   362.3  618.33
   460.2  617.73     470  617.25   548.3  608.12   558.1  607.18   577.7   606.7
     607   606.7     653   606.7     705  606.77   783.3  612.16   802.9  612.92
     842  613.72   851.8  613.52   900.8   607.5   910.6  606.81   998.7   606.7
#Mann= 3 , 0 , 0
       0      .7       0     607    .045       0     653     .08       0
#XS Ineff= 2 , 0
                           832.6          624.95
Permanent Ineff=
       F       F
Bank Sta=607,653
XS Rating Curve= 0 ,0
Exp/Cntr=0.3,0.1

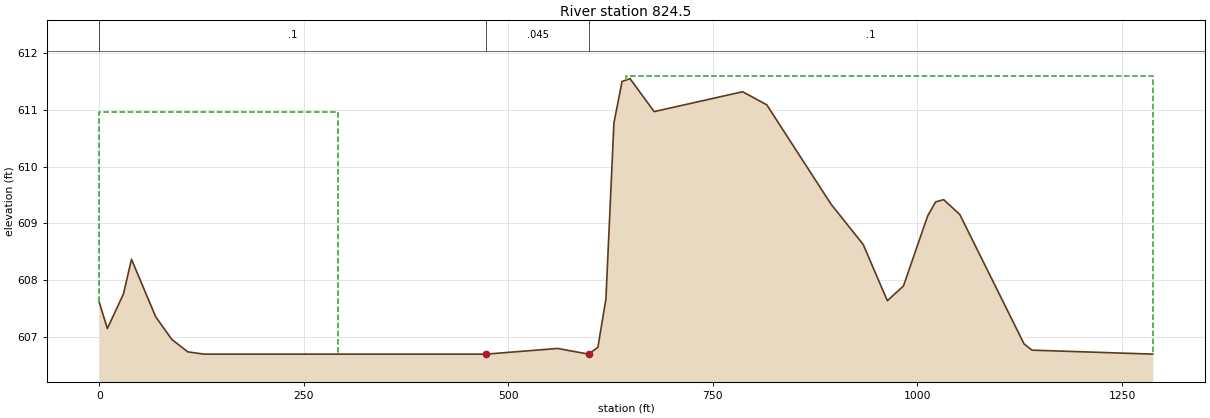
Type RM Length L Ch R = 1 ,824.5   ,823.6,824.5,827.2
XS GIS Cut Line= 2
     1511576.768      352043.119     1512188.747      353175.931
#Sta/Elev= 30
       0  607.61     9.8  607.15    29.5  607.76    39.3  608.37    68.8  607.36
    88.5  606.96   108.1  606.74   127.8   606.7     473   606.7   560.2   606.8
     598   606.7   609.4  606.82   619.2  607.67     629  610.77   638.9   611.5
   648.7  611.55   678.2  610.97   786.3  611.32   815.8  611.09   894.4  609.34
   933.7  608.63   963.2  607.64   982.9   607.9  1012.4  609.13  1022.2  609.38
    1032  609.42  1051.7  609.16  1130.3  606.88  1140.1  606.77  1287.6   606.7
#Mann= 3 , 0 , 0
       0      .1       0     473    .045       0     598      .1       0
#XS Ineff= 2 , 0
           291.5  610.97  643.58           611.6
Permanent Ineff=
       F       F
Bank Sta=473,598
XS Rating Curve= 0 ,0
Exp/Cntr=0.3,0.1

Chan Stop Cuts=-1
Use User Specified Reach Order=0
Composite Channel Slope=5

--- BENSRN.g02 (geometry) ---

Geom Title=USGS 10m DEM_copy
Program Version=4.10

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
River Reach=BENSRN          ,Main
Reach XY= 30
     1528465.411      357632.167     1529225.298       357324.68
     1529797.347      356362.874     1529691.444      355466.173
     1529523.388      355077.284     1529157.416      354740.479
     1528006.722      354882.145      1526139.36      355684.923
     1522602.555       356301.59     1521815.185      355999.984
     1521494.005      355677.718     1521163.058      355644.081
     1520213.623      353975.244     1519638.536      353661.659
     1518850.775      352927.067     1518081.461      352630.843
     1517359.429       353169.58     1516938.856      353717.757
     1516651.096      353711.247     1516437.554      354554.563
     1515887.207      354913.938     1514848.717      355016.697
      1514449.49      354627.479     1514511.339      354461.464
     1513635.688      353839.719     1513046.495      353668.278
     1512787.163       353232.08     1511882.215       352532.21
     1511417.328      352450.827     1511061.155      352637.306

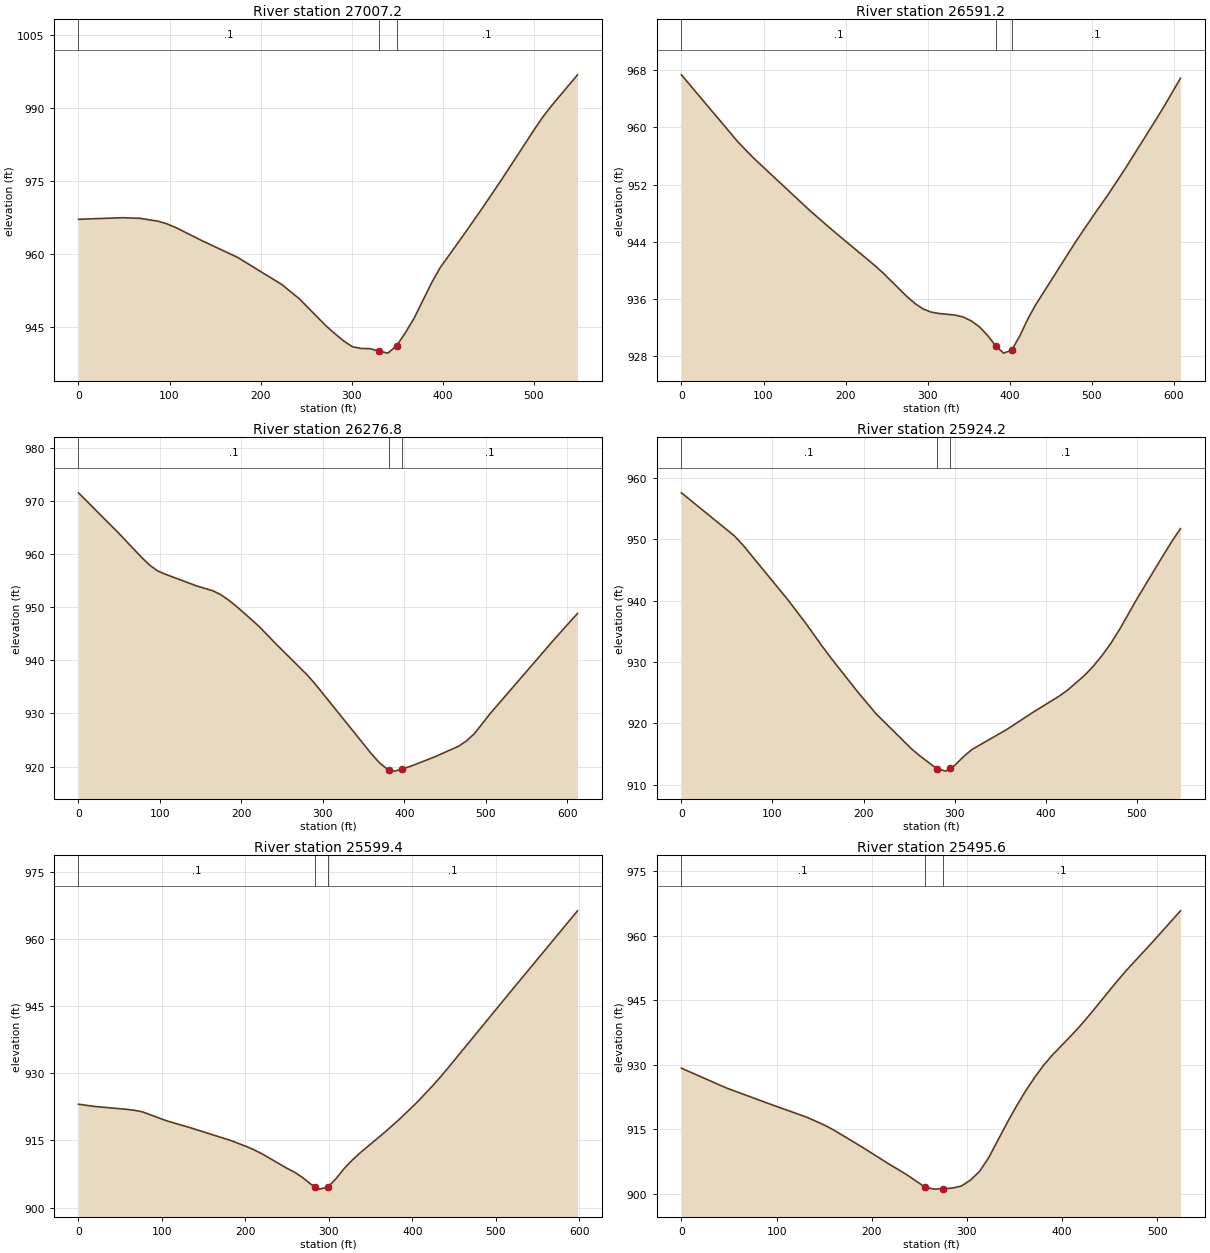
Type RM Length L Ch R = 1 ,27007.2 ,417.7,416,413.7
XS GIS Cut Line= 3
     1528651.927       357925.19     1528478.316      357599.669
     1528456.615      357421.718
#Sta/Elev= 30
       0  967.15    48.5  967.47      68  967.34    87.4  966.75    97.1  966.21
   106.8  965.46   135.9  962.72   174.8   959.3   223.3  953.72   242.7  950.76
   271.8  945.22   281.6   943.6   291.3   942.1     301  940.89   310.7  940.54
   320.4   940.5   330.1  939.99   339.8  939.58   349.5  941.08   359.2  943.81
   368.9  946.84   387.8  954.02   397.2  957.14   425.5  964.57   444.4  969.66
   463.3  974.89     501  985.71   510.4   988.3   519.9  990.58   548.2   996.9
#Mann= 3 , 0 , 0
       0      .1       0   330.1    .045       0   349.5      .1       0
Bank Sta=330.1,349.5
XS Rating Curve= 0 ,0
Exp/Cntr=0.3,0.1

Type RM Length L Ch R = 1 ,26591.2 ,317.3,314.3,310.6
XS GIS Cut Line= 3
     1528858.091      357914.339     1528892.813      357562.777
     1528756.094      357347.933
#Sta/Elev= 30
       0  967.36    68.7  957.99    88.3  955.67     157  948.31   186.4  945.39
   235.5  940.69   245.3  939.68   274.8  936.33   284.6  935.36   294.4  934.61
   304.2  934.17     314  933.97   333.6  933.75   343.5  933.47   353.3  932.92
   363.1   932.1   372.9  930.91   382.7  929.47   392.4  928.43   402.2  928.84
     412  930.79   421.8  933.17   431.6  935.21   480.6  944.07   500.2   947.4
   519.8  950.62   539.4  954.02   578.6  961.19   588.3  963.02   607.9  966.88
#Mann= 3 , 0 , 0
       0      .1       0   382.7    .045       0   402.2      .1       0
Bank Sta=382.7,402.2
XS Rating Curve= 0 ,0
Exp/Cntr=0.3,0.1

Type RM Length L Ch R = 1 ,26276.8 ,361.3,352.7,343.7
XS GIS Cut Line= 3
      1529311.65      357712.516     1529250.886      357497.673
     1528996.979      357202.534
#Sta/Elev= 30
       0  971.51    48.5  964.06    77.7  959.32    87.4   957.9    97.1  956.82
   106.8  956.18   145.6  953.96     165  953.08   174.7  952.33   184.4  951.31
   194.2   950.1   213.6  947.49   223.3  946.11   242.7  943.03   281.7  937.09
   291.4  935.37   359.5  922.41   369.3  920.73     379  919.52   381.7  919.41
   388.7  919.13   396.7   919.5   408.2  920.07   437.4  921.82   466.6  923.82
   476.3  924.82   486.1   926.2   505.5  929.98   583.4  943.82   612.6  948.81
#Mann= 3 , 0 , 0
       0      .1       0   381.7    .045       0   396.7      .1       0
Bank Sta=381.7,396.7
XS Rating Curve= 0 ,0
Exp/Cntr=0.3,0.1

Type RM Length L Ch R = 1 ,25924.2 ,329.2,324.8,319.8
XS GIS Cut Line= 4
     1529530.834       357308.87     1529409.306      357133.089
     1529272.587      357063.645     1529101.146      357005.051
#Sta/Elev= 30
       0  957.54    58.3  950.51      68  948.96   116.6  940.18     136  936.41
   155.4   932.4   165.1  930.48   194.3     925   213.7  921.58     252  915.95
   261.6  914.74   280.5  912.62   290.4  912.22   295.5   912.7     300  913.13
   309.5  914.53   319.1  915.74   357.5  919.01   386.1  921.79   414.7  924.41
   424.3  925.42   443.3  927.88   452.9  929.38   462.4  931.12   471.9  933.07
   481.5  935.34   500.5   940.3   529.2  947.34   538.7  949.62   548.2  951.71
#Mann= 3 , 0 , 0
       0      .1       0   280.5    .045       0   295.5      .1       0
Bank Sta=280.5,295.5
XS Rating Curve= 0 ,0
Exp/Cntr=0.3,0.1

Type RM Length L Ch R = 1 ,25599.4 ,98.4,103.8,108.2
XS GIS Cut Line= 4
     1529704.343      357053.608     1529561.982      356848.747
     1529476.913      356824.441     1529261.635      356678.608
#Sta/Elev= 30
       0  923.09    19.2   922.6    57.6  921.95    67.2  921.73    76.8  921.38
   105.5   919.4   134.3  917.83   182.3  915.01   201.5  913.64   211.1  912.86
   220.7  911.95   249.5  908.83   259.3  907.88   269.1  906.66     279  905.18
   283.6   904.7   288.8  904.15   298.6  904.58   308.4  906.43   318.3  908.73
   328.1  910.63   337.9  912.31   366.8  916.79   386.1     920   405.4  923.46
   424.6  927.25   434.2  929.26   443.9  931.42   520.9  948.89     598  966.23
#Mann= 3 , 0 , 0
       0      .1       0   283.6    .045       0   298.6      .1       0
Bank Sta=283.6,298.6
XS Rating Curve= 0 ,0
Exp/Cntr=0.3,0.1

Type RM Length L Ch R = 1 ,25495.6 ,382.6,382.6,382.5
XS GIS Cut Line= 3
     1529745.677      356896.544     1529595.938      356766.336
     1529307.309      356614.426
#Sta/Elev= 30
       0  929.23    47.2  924.64    94.5  920.78   132.3   917.8   151.2  915.92
   160.6   914.8     189  911.04   217.6  907.05   236.8   904.5     256  901.61
   265.6  901.14   275.2  901.25   284.8  901.38   294.4  901.87     304  903.26
   313.6  905.32   323.1  908.48   342.3  916.52   351.9  920.31   361.5  923.83
   371.1  927.01   380.7  929.92   390.3  932.37   409.5  936.75   419.1  939.05
   428.7  941.52   457.4  949.28     467  951.76   495.8  958.67   524.6  965.78
#Mann= 3 , 0 , 0
       0      .1       0     256    .045       0   275.2      .1       0
Bank Sta=256,275.2
XS Rating Curve= 0 ,0
Exp/Cntr=0.3,0.1

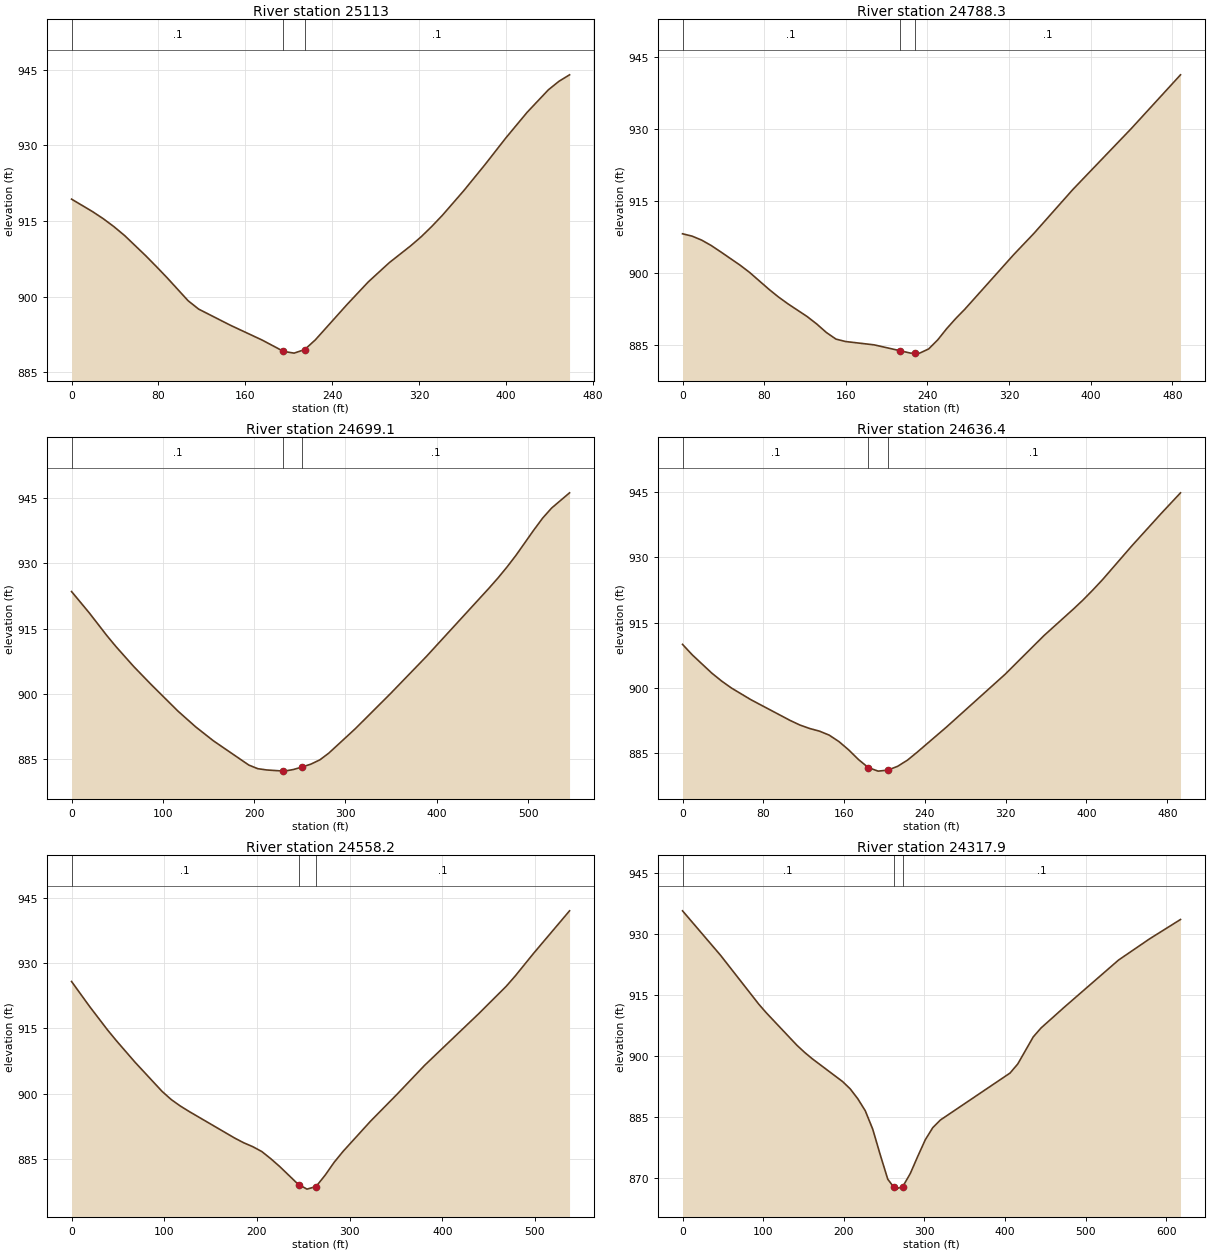
Type RM Length L Ch R = 1 ,25113   ,333.9,324.7,314.8
XS GIS Cut Line= 2
      1529943.16      356536.301     1529539.514      356319.287
#Sta/Elev= 30
       0  919.34    19.5  916.84    29.2  915.45      39  913.88    48.8  912.12
    68.3   908.1      78  905.97    87.8  903.77   107.3  899.17     117  897.51
   146.3   894.3   175.5  891.36     195  889.13   204.8  888.78   214.5  889.48
   224.3   891.4   253.5  898.42     273   902.9   292.5  906.75     312  910.06
   321.8  911.88   331.5  913.92   341.3  916.14   360.8  920.98   380.3  926.14
   399.8  931.52   419.3  936.58   438.8  941.03   448.5  942.72   458.3  944.01
#Mann= 3 , 0 , 0
       0      .1       0     195    .045       0   214.5      .1       0
Bank Sta=195,214.5
XS Rating Curve= 0 ,0
Exp/Cntr=0.3,0.1

Type RM Length L Ch R = 1 ,24788.3 ,95.9,89.2,82
XS GIS Cut Line= 4
      1530027.26      356167.757     1529842.364      356133.903
     1529753.823      356127.393        1529552.      356189.893
#Sta/Elev= 30
       0  908.21     9.4  907.72    18.8  906.89    28.2  905.76    37.6  904.43
    56.4  901.69    65.8  900.17    84.6  896.69      94  895.08   103.4  893.64
   122.2     891   131.6  889.45     141  887.69   150.4  886.32   159.8  885.82
     188  885.12   212.7  883.93   223.5  883.41   227.7  883.41   232.4  883.41
   241.2  884.28   250.1  886.17     259  888.53   267.9  890.64   276.8  892.57
   324.8  903.94     344  908.21   382.4  917.39     440  930.13     488  941.24
#Mann= 3 , 0 , 0
       0      .1       0   212.7    .045       0   227.7      .1       0
Bank Sta=212.7,227.7
XS Rating Curve= 0 ,0
Exp/Cntr=0.3,0.1

Type RM Length L Ch R = 1 ,24699.1 ,68.9,62.7,57
XS GIS Cut Line= 3
     1530038.646      355987.256     1529745.677        356056.7
     1529515.643      356139.166
#Sta/Elev= 30
       0  923.52    19.4  918.62    38.8  913.37    48.6  910.89      68  906.32
    87.4  902.12   116.6  896.05     136  892.43   155.4  889.23   194.2  883.66
     204  882.83   213.7  882.54   232.1  882.28   233.1  882.27   242.8  882.63
   252.5  883.21   262.2  883.88     272  884.86   281.7  886.39   310.9  892.03
     350  900.22   389.1   908.7   457.5  924.35   467.3  926.69     477  929.16
   486.8  931.84   506.4  937.67   516.1  940.41   525.9  942.71   545.5   946.2
#Mann= 3 , 0 , 0
       0      .1       0   232.1    .045       0   252.5      .1       0
Bank Sta=232.1,252.5
XS Rating Curve= 0 ,0
Exp/Cntr=0.3,0.1

Type RM Length L Ch R = 1 ,24636.4 ,79.1,78.2,77.2
XS GIS Cut Line= 3
     1529955.646      355895.622     1529749.916      356003.695
     1529510.333      356106.559
#Sta/Elev= 30
       0     910     9.7  907.58      29  903.39    38.7  901.57    48.4  899.97
    67.8  897.27   106.5  892.52   116.2  891.46   125.9  890.66   135.6  890.05
   145.2  889.14   154.9  887.65   164.6  885.73   174.3  883.51     184  881.67
   193.7  880.86   203.3  881.09     213  881.97   222.7  883.38   232.4  885.22
   261.4     891   319.3   903.1   357.9  912.02   386.9  918.09   396.6  920.21
   406.2  922.48   415.9  924.88   444.8  932.62   473.8  940.05   493.1  944.84
#Mann= 3 , 0 , 0
       0      .1       0     184    .045       0   203.3      .1       0
Bank Sta=184,203.3
XS Rating Curve= 0 ,0
Exp/Cntr=0.3,0.1

Type RM Length L Ch R = 1 ,24558.2 ,235.4,240.3,245.4
XS GIS Cut Line= 2
     1529959.552      355794.059     1529494.708      356063.591
#Sta/Elev= 30
       0  925.73    19.5  919.99    39.1  914.54    48.8  912.04    68.4  907.23
    97.7  900.51   107.5  898.65   117.2  897.18     127  895.89   175.8  889.83
   185.6  888.74   195.4  887.84   205.2  886.72   214.9  885.08   224.7  883.25
   244.2  879.26   245.3  879.13     254  878.09   263.8  878.69   273.6  881.29
   283.3  884.24   293.1  886.79   322.4  893.64   351.7  899.97     381  906.51
   439.6  918.41     469  924.64   478.7     927   498.2  932.12   537.3  941.95
#Mann= 3 , 0 , 0
       0      .1       0   245.3    .045       0   263.8      .1       0
Bank Sta=245.3,263.8
XS Rating Curve= 0 ,0
Exp/Cntr=0.3,0.1

Type RM Length L Ch R = 1 ,24317.9 ,315.4,315,312.4
XS GIS Cut Line= 4
     1529962.691      355683.436     1529745.677      355672.586
     1529648.021      355702.968     1529428.837      355904.791
#Sta/Elev= 30
       0  935.75    47.2   924.8    94.5   912.8   103.9  910.66   141.7  902.71
   151.2  900.96   160.6   899.4   198.4  893.76   207.8  891.98   217.3  889.53
   226.6  886.57   235.9  882.01   245.2  875.71   254.5  869.73   262.1  867.74
   263.8  867.29   273.1  867.92   282.4  871.12   291.7  875.36     301  879.42
   310.3  882.41   319.6  884.27   406.1  895.84   415.7  898.08   434.9  904.74
   444.5  906.92   473.3  912.03   540.6  923.63   579.1  928.85   617.5  933.62
#Mann= 3 , 0 , 0
       0      .1       0   262.1    .045       0   273.1      .1       0
Bank Sta=262.1,273.1
XS Rating Curve= 0 ,0
Exp/Cntr=0.3,0.1