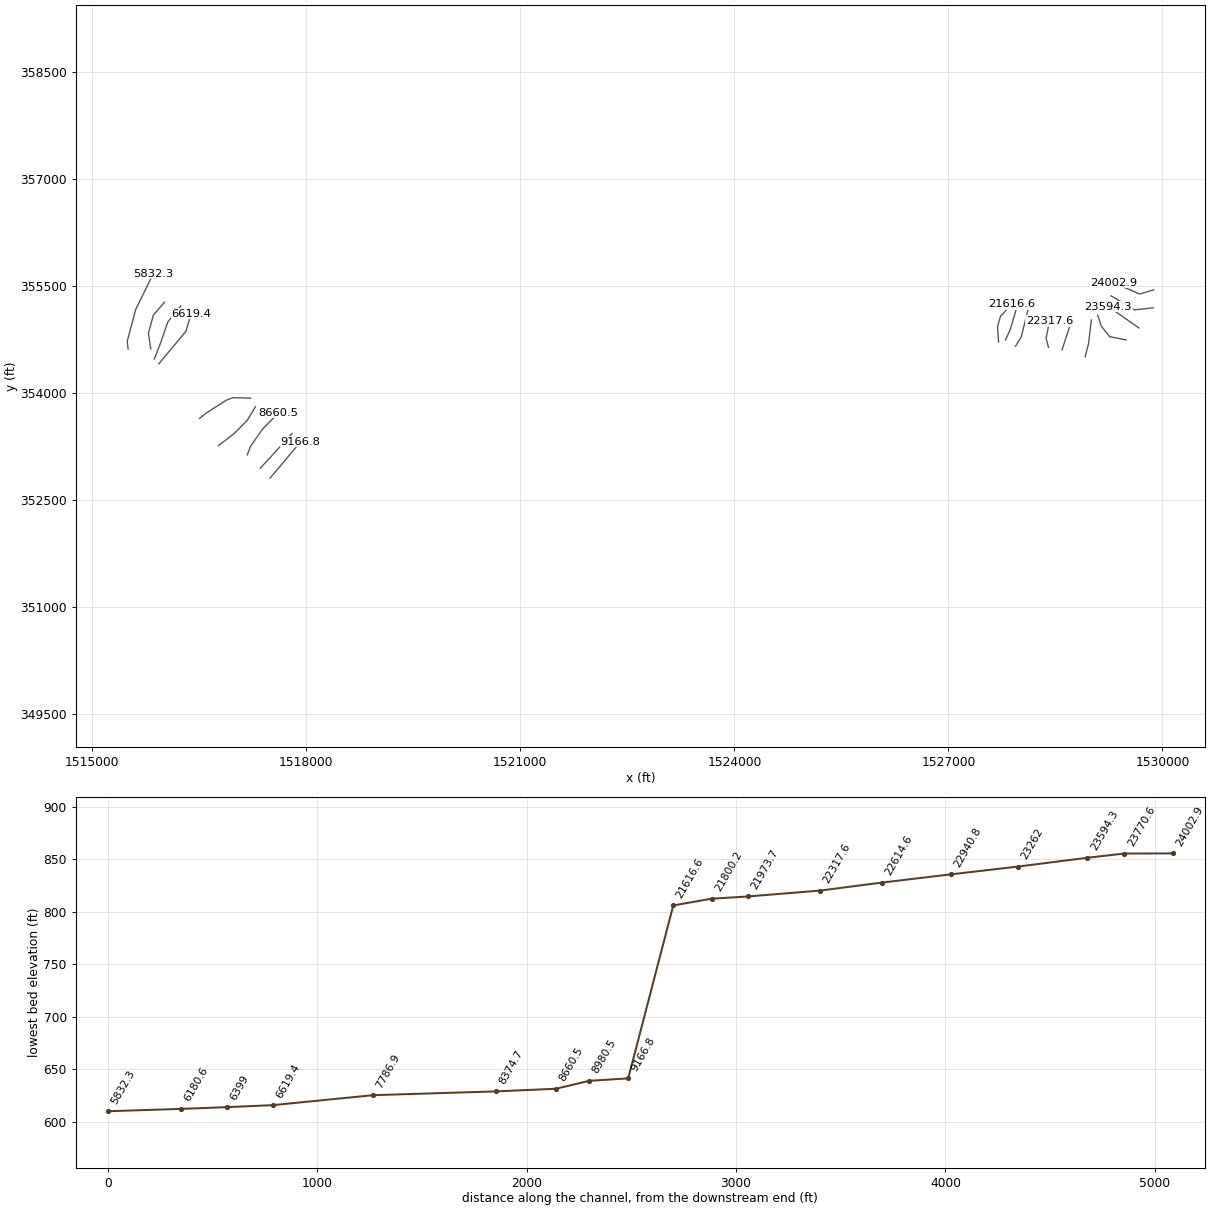
HEC-RAS study BENSRN.prj: BENSRN

--- BENSRN.g02 (geometry) --- (continued)

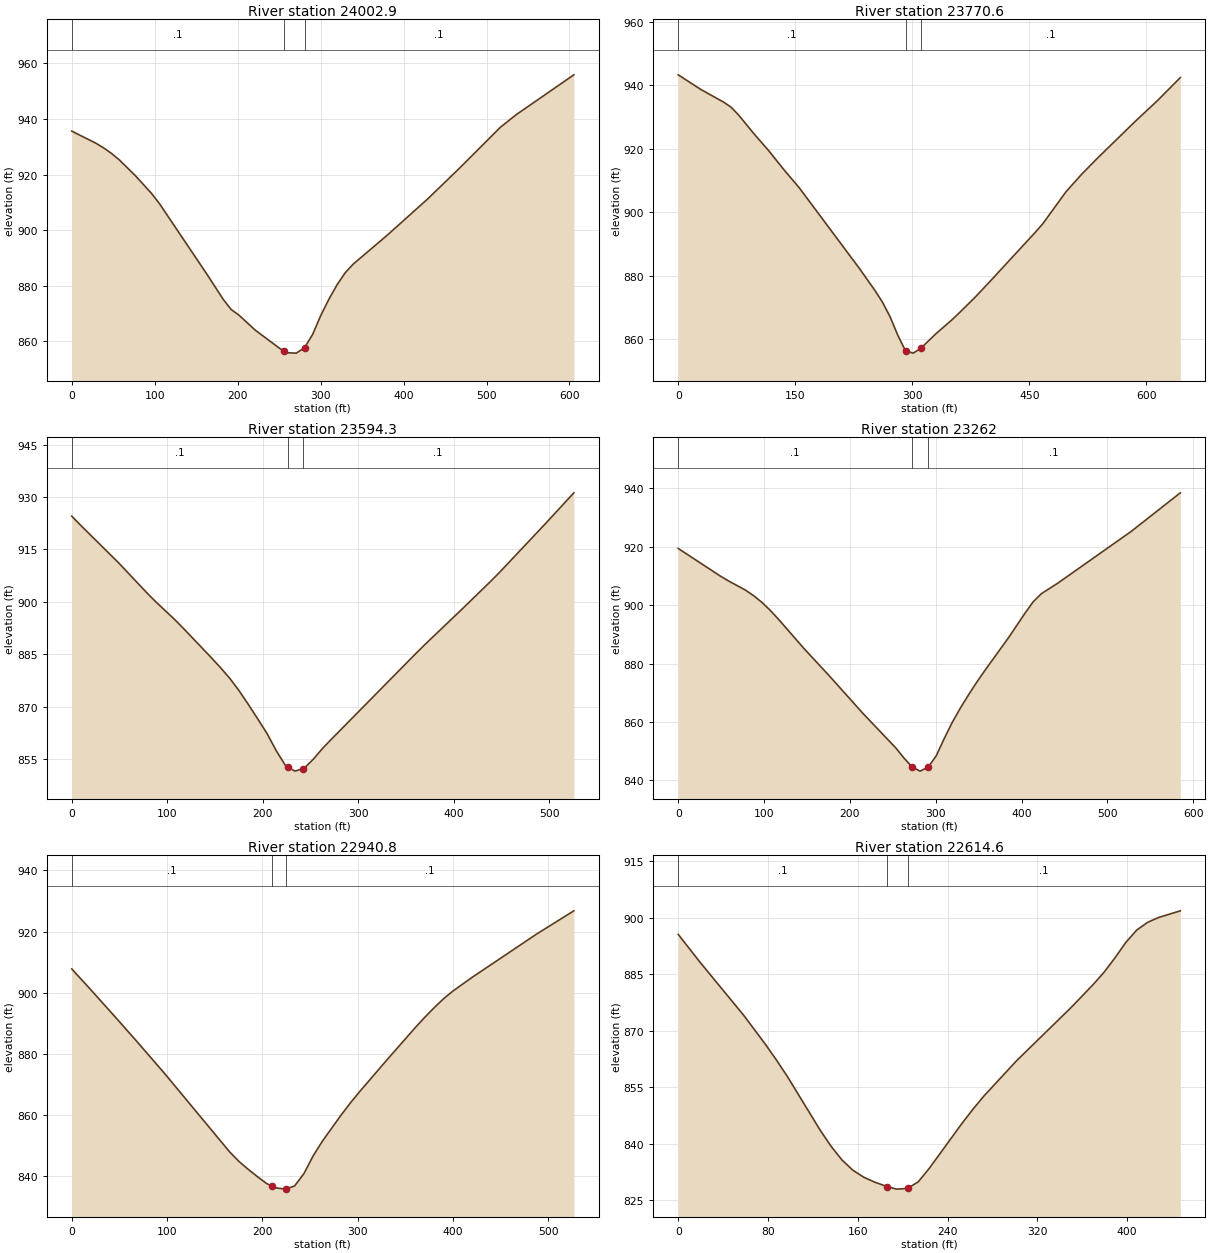
Type RM Length L Ch R = 1 ,24002.9 ,235.9,232.3,229.1
XS GIS Cut Line= 3
     1529875.886      355444.721     1529682.743      355386.127
      1529311.65      355544.548
#Sta/Elev= 30
       0  935.63    28.8  931.32    38.4   929.6    48.1  927.56    57.7  925.17
    76.9  919.51    96.1  913.22   105.7  909.53   163.4  883.89   182.6  875.04
   192.2  871.39   201.8   869.3   221.5  863.88     251  857.31   256.2  856.51
   260.9  855.79   270.7  855.68   280.6  857.63   290.4  862.42   300.2  869.24
   310.1  875.14   319.9  880.33   329.8  884.68   339.6  887.82     379   897.8
   428.2  910.96   467.6  922.33   516.8  937.04   536.4  941.67   605.3   955.9
#Mann= 3 , 0 , 0
       0      .1       0   256.2    .045       0   280.6      .1       0
Bank Sta=256.2,280.6
XS Rating Curve= 0 ,0
Exp/Cntr=0.3,0.1

Type RM Length L Ch R = 1 ,23770.6 ,177.6,176.3,175.1
XS GIS Cut Line= 3
     1529869.375      355192.985     1529608.959      355164.773
     1529281.268      355360.086
#Sta/Elev= 30
       0  943.22    29.1  938.59    58.2  934.62    67.9  932.99    77.6   930.5
      97  924.67   116.4  919.19   135.8  913.23   155.2  907.61   232.8  882.02
   252.2  875.25   261.9  871.54   271.7   866.9   281.5  861.12   291.3  856.27
   301.1  855.56   310.8  857.08   330.4  861.71     350  865.89   359.8  868.16
   379.3  872.88   398.9  877.98   457.6  893.63   467.4  896.38   496.7  906.32
   516.3  911.72   535.8  916.62   584.7  928.34   614.1  935.09   643.4  942.35
#Mann= 3 , 0 , 0
       0      .1       0   291.3    .045       0   310.8      .1       0
Bank Sta=291.3,310.8
XS Rating Curve= 0 ,0
Exp/Cntr=0.3,0.1

Type RM Length L Ch R = 1 ,23594.3 ,339,332.3,325.2
XS GIS Cut Line= 2
     1529671.893      354910.867     1529240.035      355210.346
#Sta/Elev= 30
       0   924.5     9.7  921.78    48.7  911.24    77.9  902.76    87.6  900.08
     107  895.11   116.8   892.4     146  884.02   155.7  881.14   165.4  878.08
   175.2  874.51   184.9  870.59   194.6  866.49   204.4  862.29   214.1  857.34
   223.8  853.08   226.6  852.64   233.6  851.53   241.6  852.21   243.3  852.35
     253     855   262.8  858.13   272.5  860.87   360.1  885.18   369.8  887.81
   408.8  897.98     438  905.74   447.7   908.4   496.3  922.52   525.5  931.18
#Mann= 3 , 0 , 0
       0      .1       0   226.6    .045       0   241.6      .1       0
Bank Sta=226.6,241.6
XS Rating Curve= 0 ,0
Exp/Cntr=0.3,0.1

Type RM Length L Ch R = 1 ,23262   ,340.2,321.2,301.8
XS GIS Cut Line= 4
     1529489.601      354743.766     1529259.566      354789.339
     1529142.379      354936.909     1529092.466      355090.989
#Sta/Elev= 30
       0  919.43    48.9     910    58.6   908.3    78.2  905.18    87.9  903.23
    97.7  900.91   107.5  898.13   117.2  895.04   146.6  885.11   175.9  875.81
     215  862.96   253.4  851.09   262.8  847.67   272.2  844.62   281.6  843.12
     291  844.43   300.5  848.33   309.9   854.3   319.3  859.87   328.7  864.75
   338.2  869.27   347.6  873.53     357  877.52   385.3  889.07   404.1   897.3
   413.5  901.15     423  903.93     442   907.5   527.8   925.3   584.9   938.5
#Mann= 3 , 0 , 0
       0      .1       0   272.2    .045       0     291      .1       0
Bank Sta=272.2,291
XS Rating Curve= 0 ,0
Exp/Cntr=0.3,0.1

Type RM Length L Ch R = 1 ,22940.8 ,330.5,326.2,321.6
XS GIS Cut Line= 3
     1528916.684      354505.051     1528964.427      354693.853
      1529003.49      355023.714
#Sta/Elev= 30
       0  907.78    19.5  901.14    48.7  890.98    68.2  884.08    97.4  873.57
   165.5  847.97   175.3  844.82     185  842.23   194.8   839.8   204.5  837.54
   210.3  836.69   214.3  836.11     224  835.71   225.3  835.85   233.8  836.74
   243.6  840.77   253.4  846.64   263.1  851.44   282.7  859.97   292.4  863.93
   302.2  867.65   331.5  878.28   360.8  888.69   370.6     892   380.4  895.11
   390.1     898   399.9  900.52   419.4  904.87   487.8  919.19   526.9   926.8
#Mann= 3 , 0 , 0
       0      .1       0   210.3    .045       0   225.3      .1       0
Bank Sta=210.3,225.3
XS Rating Curve= 0 ,0
Exp/Cntr=0.3,0.1

Type RM Length L Ch R = 1 ,22614.6 ,293.8,297,298.5
XS GIS Cut Line= 2
     1528593.334      354607.048     1528732.223      355032.395
#Sta/Elev= 30
       0  895.57    19.4  888.19    58.4  874.07    77.8  866.34    87.5  862.23
    97.3  857.83   126.4  843.64   136.2  839.33   145.9  835.69   155.6  832.98
   165.4   831.1   175.1   829.8   186.4  828.61   194.5  827.95   204.3  828.12
     214  829.92   223.7  833.47   252.9  845.41   262.6  849.15   272.4  852.67
   301.5  862.03   350.2  876.19   369.6  882.21   379.4   885.5   389.1  889.31
   398.8  893.41   408.5   896.7   418.3  898.77     428  900.05   447.4  901.82
#Mann= 3 , 0 , 0
       0      .1       0   186.4    .045       0   204.3      .1       0
Bank Sta=186.4,204.3
XS Rating Curve= 0 ,0
Exp/Cntr=0.3,0.1

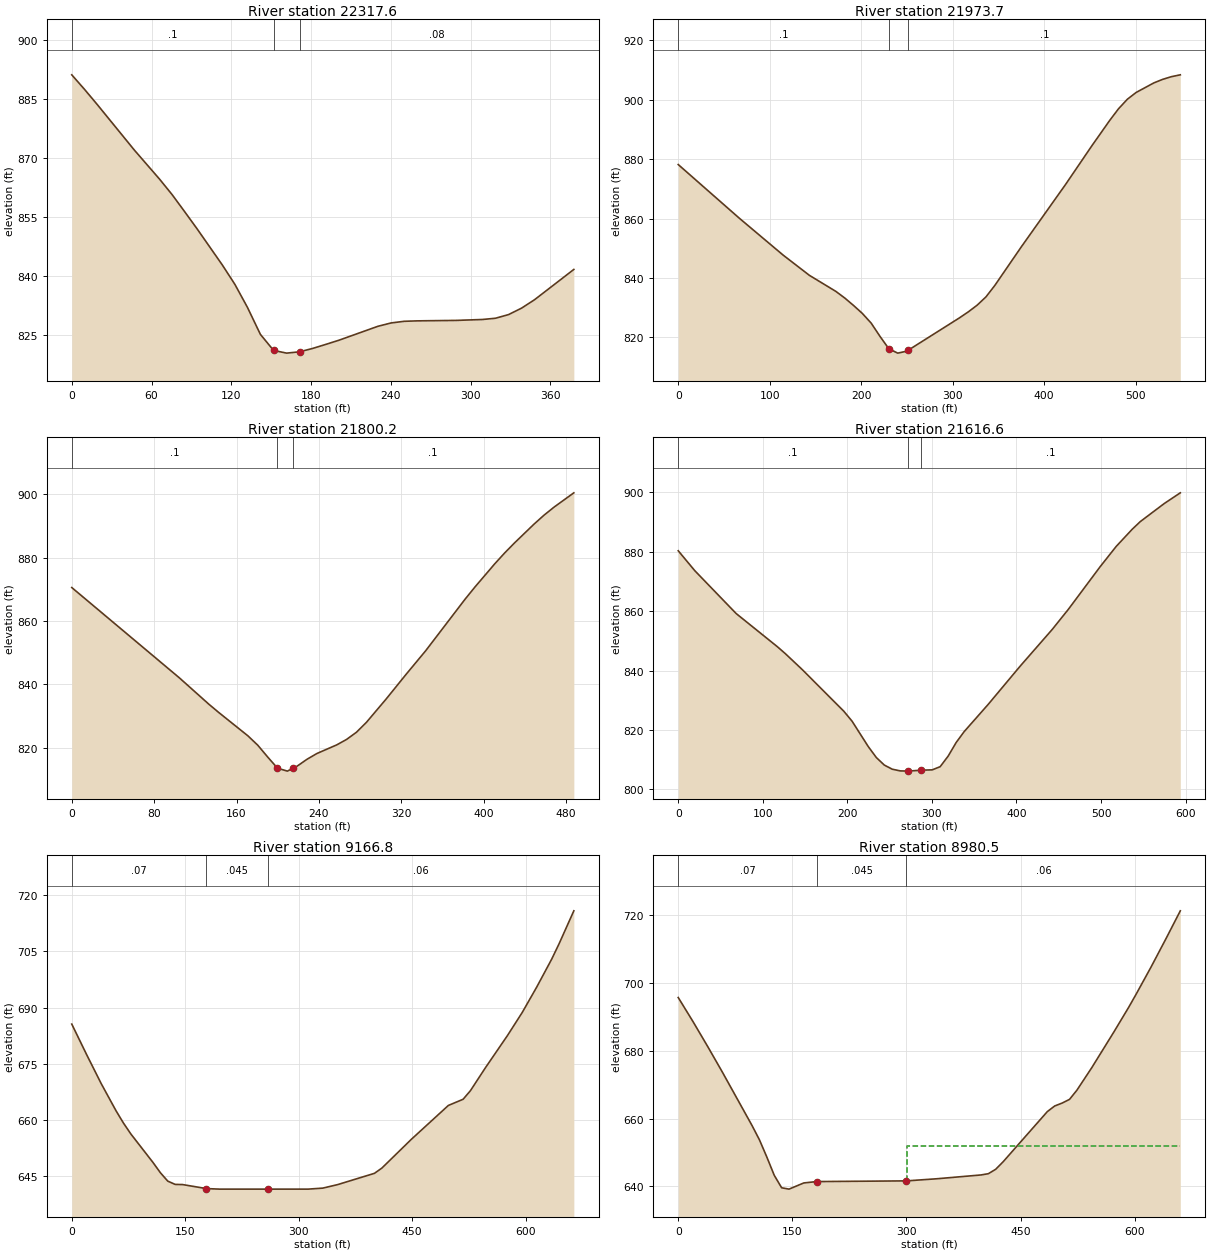
Type RM Length L Ch R = 1 ,22317.6 ,344.4,344,342.4
XS GIS Cut Line= 3
     1528402.361        354639.6     1528369.809      354767.638
     1528417.552      355008.523
#Sta/Elev= 29
       0  891.04     9.4  887.42    18.9   883.6    47.2  871.86    66.1   864.5
    75.5  860.58    84.9  856.26    94.4  851.83   113.2  842.73   122.7  837.78
   132.1  831.96   141.9  825.06   151.8  820.99   161.6  820.29   171.4  820.63
   181.2  821.48     191   822.5   200.9  823.56   230.3  827.11   240.2  827.96
     250  828.38   259.8  828.49   289.3  828.61   308.9  828.84   318.8  829.16
   328.6  830.09   338.4  831.73   348.2  833.88   377.7  841.57
#Mann= 3 , 0 , 0
       0      .1       0   151.8    .045       0   171.4     .08       0
Bank Sta=151.8,171.4
XS Rating Curve= 0 ,0
Exp/Cntr=0.3,0.1

Type RM Length L Ch R = 1 ,21973.7 ,174.3,173.5,172.4
XS GIS Cut Line= 3
     1527940.122      354654.791     1528020.417      354784.999
     1528115.903      355169.114
#Sta/Elev= 30
       0  878.18    66.9  860.08   114.7  847.69   143.4  840.88   172.3  835.48
   181.9  833.28   191.6  830.75   201.2  828.08   210.9   824.8   220.6  820.31
   230.2  816.17   239.9   814.7   249.5  815.33   251.5   815.7   307.4  826.57
   317.1   828.6   326.7  830.83   336.4  833.64     346  837.46     375  850.47
   423.3  871.44   452.2  884.53   471.6  893.02   481.2  896.93   490.9  900.15
   500.5  902.44   519.8  905.65   529.5  906.85   539.1  907.76   548.8  908.38
#Mann= 3 , 0 , 0
       0      .1       0   230.2    .045       0   251.5      .1       0
Bank Sta=230.2,251.5
XS Rating Curve= 0 ,0
Exp/Cntr=0.3,0.1

Type RM Length L Ch R = 1 ,21800.2 ,183.2,183.6,183.6
XS GIS Cut Line= 3
     1527800.611      354742.222     1527870.055      354898.472
     1527959.031      355202.291
#Sta/Elev= 30
       0  870.52   104.5  842.01     133  833.73   142.5  831.14     171  823.72
   180.6  820.76   190.2  817.04   199.5   813.6   199.8  813.49   209.4  812.56
   214.5  813.41     219  814.16   228.6  816.33   238.1  818.13   257.3  820.84
   266.9  822.57   276.5  824.84   286.1  827.94   305.3  835.32   324.5  843.04
   343.7  850.56     382  866.85   391.6   870.7   410.8  878.01   420.4  881.43
     430  884.61   449.2  890.62   458.8   893.4   468.4  895.91   487.6  900.42
#Mann= 3 , 0 , 0
       0      .1       0   199.5    .045       0   214.5      .1       0
Bank Sta=199.5,214.5
XS Rating Curve= 0 ,0
Exp/Cntr=0.3,0.1

Type RM Length L Ch R = 1 ,21616.6 ,220.1,215.2,212
XS GIS Cut Line= 4
     1527703.577      354713.384     1527688.386      354928.228
     1527729.618      355073.627     1527883.698      355240.728
#Sta/Elev= 30
       0  880.28    19.6  873.58    68.5  859.17   117.5  847.95   127.3  845.51
   146.8  840.28   195.8  826.32   205.6  822.95   224.8   814.4   234.3  810.73
   243.7   808.2   253.2   806.8   262.6  806.24   271.9  806.16   286.9  806.47
   300.4  806.59   309.8  807.66   319.3  811.24   328.7  815.78   338.2  819.46
   366.5  828.58   404.4  841.47   442.3  853.81   461.2  860.51   499.1  874.96
     518  881.75     537  887.54   546.5   890.1   574.9  896.19   593.8  899.77
#Mann= 3 , 0 , 0
       0      .1       0   271.9    .045       0   286.9      .1       0
Bank Sta=271.9,286.9
XS Rating Curve= 0 ,0
Exp/Cntr=0.3,0.1

Type RM Length L Ch R = 1 ,9166.8  ,187.2,186.3,185.3
XS GIS Cut Line= 2
     1517493.507      352809.124     1517921.025      353316.936
#Sta/Elev= 30
       0  685.58    19.5  677.49      39  669.65    58.6   662.4    68.3  659.16
    78.1  656.24   107.4  648.62   117.1   645.9   126.9  643.64   136.7  642.76
   146.4  642.72     178 641.647   195.2   641.5     260   641.5   312.4   641.5
   331.9  641.77   351.4   642.7   400.2  645.72     410  647.12     449  654.81
   497.9  663.85   517.4   665.5   527.1   667.8   546.7  673.86     576  682.51
   595.5  688.66     615  695.57   634.5  702.92   644.3  707.04   663.8  715.83
#Mann= 3 , 0 , 0
       0     .07       0     178    .045       0     260     .06       0
Bank Sta=178,260
XS Rating Curve= 0 ,0
Exp/Cntr=0.3,0.1

Type RM Length L Ch R = 1 ,8980.5  ,159.6,159.2,158.8
XS GIS Cut Line= 2
     1517355.197      352945.897      1517800.51      353432.876
#Sta/Elev= 30
       0  695.68    19.4  688.59    38.8  681.21    58.2  673.61      97  657.94
   106.8  653.69   116.4  648.67   126.2  643.26   135.9  639.58   145.6  639.18
     165     641     182 641.408     300 641.613   339.6  642.23   397.9  643.36
   407.6  643.73   417.3  645.04     427  647.24   485.2  662.06   494.9  663.71
   504.6  664.56   514.3  665.65     524  668.36   543.4  674.95   572.6  685.53
     592  692.78   601.7  696.61   621.1  704.53   640.5  712.79   659.9  721.25
#Mann= 3 , 0 , 0
       0     .07       0     182    .045       0     300     .06       0
#XS Ineff= 2 , 0
                          300.92           651.8
Permanent Ineff=
       F       F
Bank Sta=182,300
XS Rating Curve= 0 ,0
Exp/Cntr=0.3,0.1

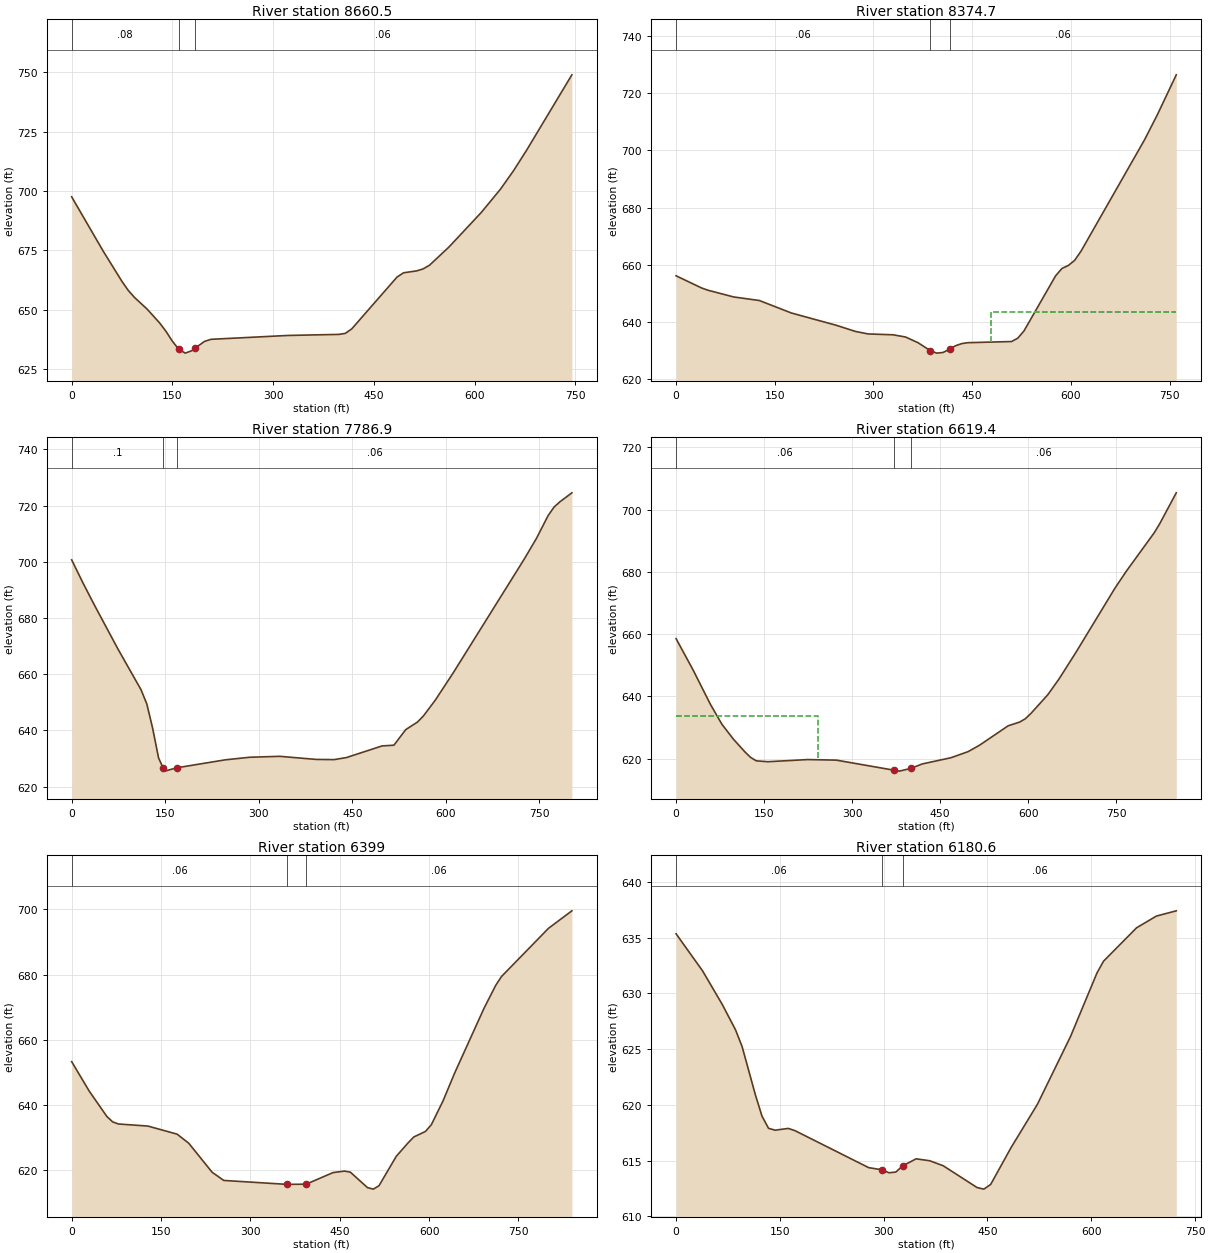
Type RM Length L Ch R = 1 ,8660.5  ,289.7,285.8,282.2
XS GIS Cut Line= 4
     1517172.905      353133.397      1517219.78      353255.793
     1517383.843      353490.168      1517613.01      353724.543
#Sta/Elev= 30
       0  697.51    46.8   674.7    74.9  661.86    84.3  658.06    93.6  655.09
   112.3   650.2   131.1  644.31   140.6  640.76   150.1  636.58   159.7  633.19
   169.2  631.61   178.8  632.62   183.3   633.6   197.8  636.54   207.4  637.43
   321.8  639.06   398.1  639.51   407.6  639.94   417.2  641.85   484.6  663.69
   494.3  665.49   513.6  666.28   523.2   667.1   532.8  668.64   561.8  676.32
     610  690.91   638.9  700.84   658.2  708.58   677.5  717.14     745  748.97
#Mann= 3 , 0 , 0
       0     .08       0   159.7    .045       0   183.3     .06       0
Bank Sta=159.7,183.3
XS Rating Curve= 0 ,0
Exp/Cntr=0.3,0.1

Type RM Length L Ch R = 1 ,8374.7  ,593,587.7,582.3
XS GIS Cut Line= 4
      1516769.26      353263.605     1516993.218       353435.48
     1517172.905      353617.772     1517287.489      353807.876
#Sta/Elev= 30
       0  656.15    38.9  651.88    48.7  651.09    87.6  648.75   126.6  647.51
   175.2  643.15   243.4  638.86   272.6   636.7   291.8  635.83   329.7  635.53
   348.7  634.76   367.6  632.78   386.6  629.96   396.1  629.12   405.6  629.34
   416.2  630.55   424.5  631.68     434  632.44   443.5  632.77   509.8  633.17
   519.3  634.34   528.8   636.9   576.9  656.17   586.5  658.72   596.2  659.76
   605.8  661.56   615.5  664.78     712  703.69   731.3  712.36   760.2  726.39
#Mann= 3 , 0 , 0
       0     .06       0   386.6    .045       0   416.2     .06       0
#XS Ineff= 2 , 0
                          478.75           643.4
Permanent Ineff=
       F       F
Bank Sta=386.6,416.2
XS Rating Curve= 0 ,0
Exp/Cntr=0.3,0.1

Type RM Length L Ch R = 1 ,7786.9  ,485.6,478.9,471.9
XS GIS Cut Line= 5
     1516503.635      353643.813     1516605.197      353724.543
     1516883.843      353901.626     1516972.385       353935.48
      1517219.78      353927.668
#Sta/Elev= 30
       0   700.7    18.5  692.32    37.1  684.34    74.1  669.02   111.2  654.49
   120.5  649.43   129.7  640.92   139.4  630.17  147.03  626.46   149.2   625.5
   168.6  626.69   246.3  629.52   285.1  630.43   333.7  630.77   391.9  629.67
     421   629.6   440.5  630.32   497.8  634.47   516.8  634.73   535.7  640.26
   554.7  642.99   564.2  645.16   583.2  650.78   611.8  660.44     726  701.04
   745.1  708.22   764.1  716.45   773.6  719.48   783.2   721.4   802.2  724.56
#Mann= 3 , 0 , 0
       0      .1       0  147.03    .045       0   168.6     .06       0
Bank Sta=147.03,168.6
XS Rating Curve= 0 ,0
Exp/Cntr=0.3,0.1

Type RM Length L Ch R = 1 ,6619.4  ,211.5,220.4,228.8
XS GIS Cut Line= 3
     1515931.253      354407.586     1516313.198      354864.184
     1516386.114      355110.711
#Sta/Elev= 30
       0  658.55    29.3  648.38    58.6  637.43    78.1  631.07    97.6   626.3
   117.1  622.23   126.9  620.43   136.6  619.32   156.1  619.03   224.4  619.72
   273.2  619.54   370.7  616.33   380.6  616.01   400.1  616.89   419.6  618.32
   468.4  620.31   497.7  622.27   517.2  624.34     566  630.57   585.5  631.76
   595.3  632.84   604.8  634.55   633.4  640.52   652.4  645.54     681  654.01
   747.6  674.66   766.7  680.04   814.3  692.39   823.8   695.3   852.4  705.36
#Mann= 3 , 0 , 0
       0     .06       0   370.7    .045       0   400.1     .06       0
#XS Ineff= 2 , 0
           241.5   633.6
Permanent Ineff=
       F       F
Bank Sta=370.7,400.1
XS Rating Curve= 0 ,0
Exp/Cntr=0.3,0.1

Type RM Length L Ch R = 1 ,6399    ,217.5,218.4,219.7
XS GIS Cut Line= 4
     1515870.822      354478.015     1515959.364      354707.181
     1516060.926      354998.848     1516240.614      355220.202
#Sta/Elev= 30
       0  653.26    29.5   644.2      59  636.44    68.8  634.76    78.6  634.11
   127.8  633.48   176.9     631   196.5  628.21   235.8  619.29   255.3  616.78
   361.5  615.57   393.6  615.63   438.7  619.19     458  619.65   467.7  619.33
   496.6  614.57   506.3  614.11   515.9  615.17   544.9   624.2   564.4  628.26
   574.2  630.12   593.8  631.82   603.7  633.88   623.3  641.19     643  649.82
   692.2  669.67   711.8   676.7   721.6  679.42   800.3  694.19   839.6  699.57
#Mann= 3 , 0 , 0
       0     .06       0   361.5    .045       0   393.6     .06       0
Bank Sta=361.5,393.6
XS Rating Curve= 0 ,0
Exp/Cntr=0.3,0.1

Type RM Length L Ch R = 1 ,6180.6  ,350.4,348.3,342.6
XS GIS Cut Line= 4
     1515820.142      354619.392     1515787.156      354836.406
       1515856.6      355091.614      1516012.85       355272.17
#Sta/Elev= 30
       0  635.36    38.2  632.04    66.8  629.01    85.9  626.74    95.4  625.24
   114.5  620.93   124.1     619   133.6   617.9   143.2  617.73   162.2  617.89
   171.8  617.69   278.3  614.37   297.9  614.17   307.7  613.91   317.5  613.97
   327.3  614.52   346.8  615.16   366.4  614.99     386  614.54     435  612.58
   444.8  612.44   454.6  612.86     484  616.16   522.2  620.06     570  626.14
   608.2  631.84   617.7   632.9   665.5   635.9   694.1  636.95   722.8  637.42
#Mann= 3 , 0 , 0
       0     .06       0   297.9    .045       0   327.3     .06       0
Bank Sta=297.9,327.3
XS Rating Curve= 0 ,0
Exp/Cntr=0.3,0.1

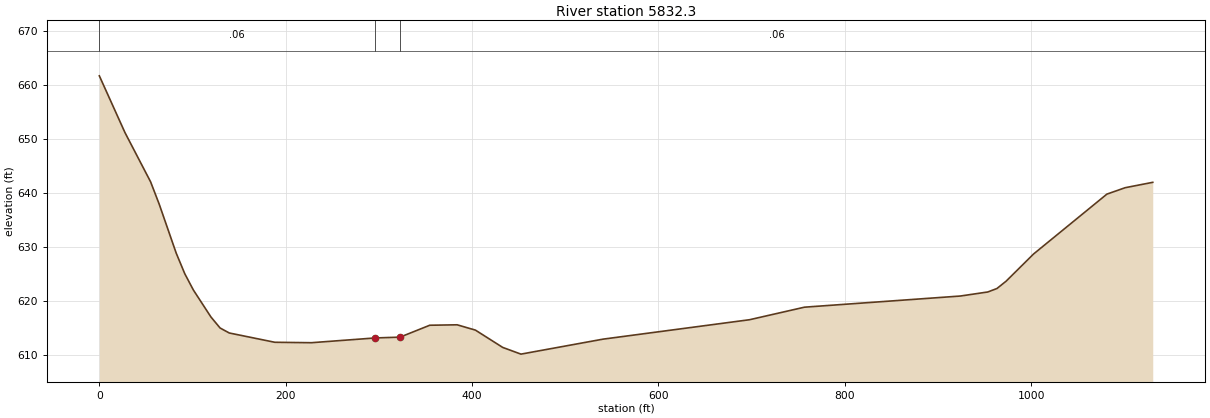
Type RM Length L Ch R = 1 ,5832.3  ,113.6,114.4,115.2
XS GIS Cut Line= 4
     1515502.434      354614.184     1515490.281      354723.559
     1515608.337      355168.003     1515854.864      355671.475
#Sta/Elev= 30
       0  661.67    27.5  651.18      55  642.08    64.2  637.97    82.5  628.89
    91.7  625.08   100.9  622.08   119.8  617.08   129.6  615.05   139.4  614.13
   188.3  612.41   227.5  612.33     296  613.21   322.7  613.36   354.6  615.56
     384  615.64   403.6  614.66   432.9  611.46   452.5  610.22   540.6  612.99
   697.8  616.58   756.8   618.9     924  620.96   953.5  621.71   963.3  622.35
   973.1   623.7  1002.6  628.73  1081.3   639.8    1101  640.99  1130.5  641.98
#Mann= 3 , 0 , 0
       0     .06       0     296    .045       0   322.7     .06       0
Bank Sta=296,322.7
XS Rating Curve= 0 ,0
Exp/Cntr=0.3,0.1