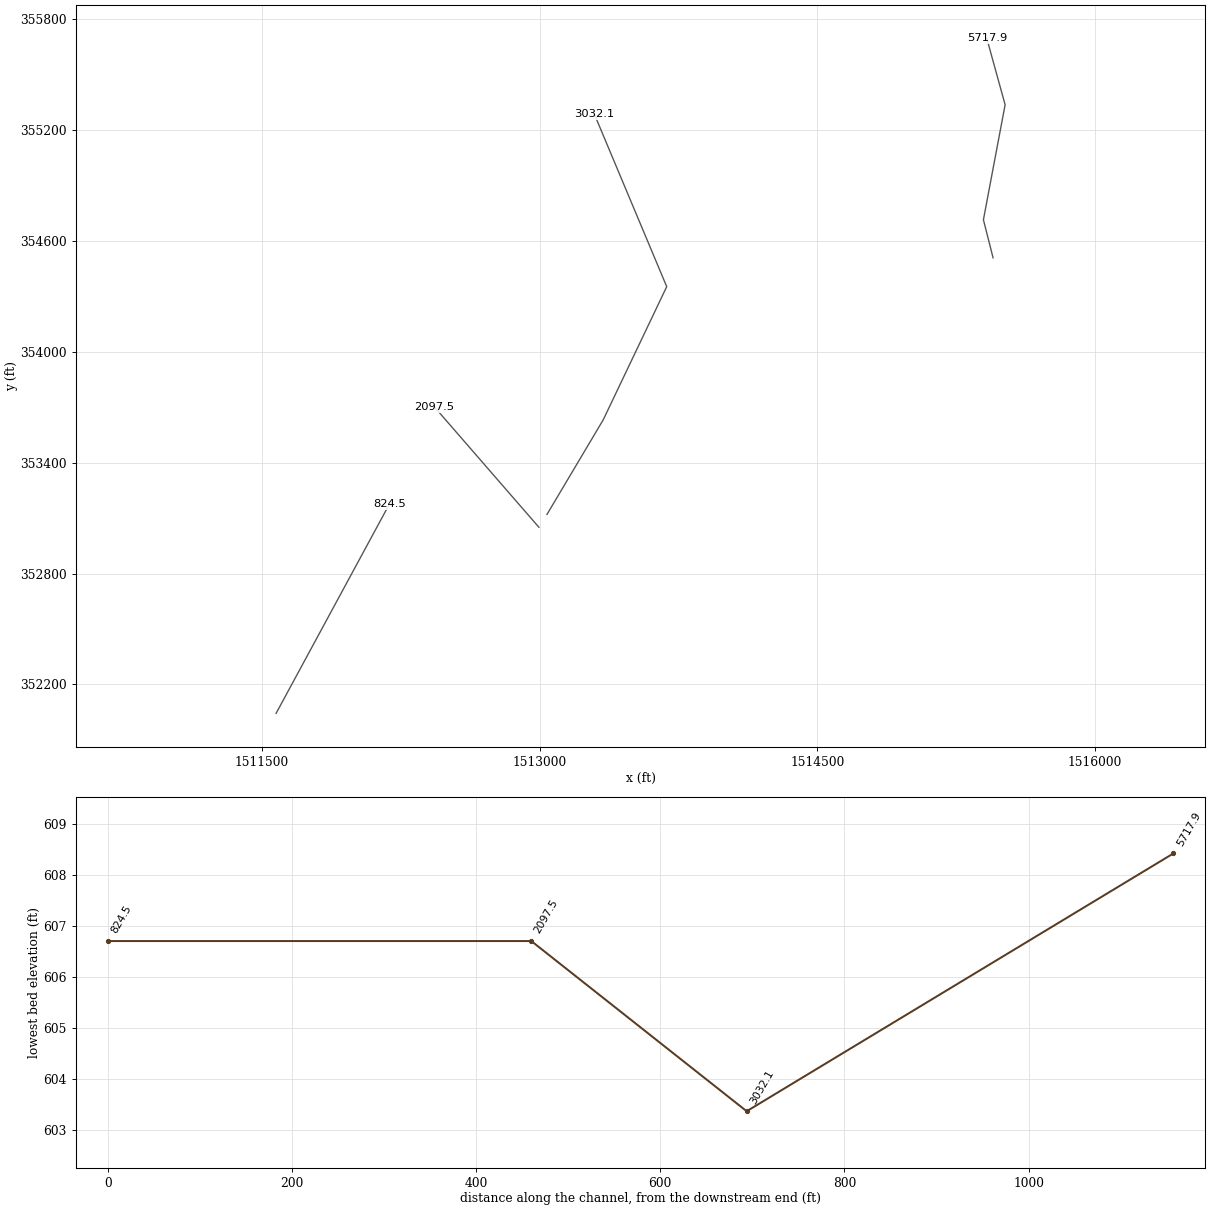
HEC-RAS study BENSRN.prj: BENSRN

--- BENSRN.g02 (geometry) --- (continued)

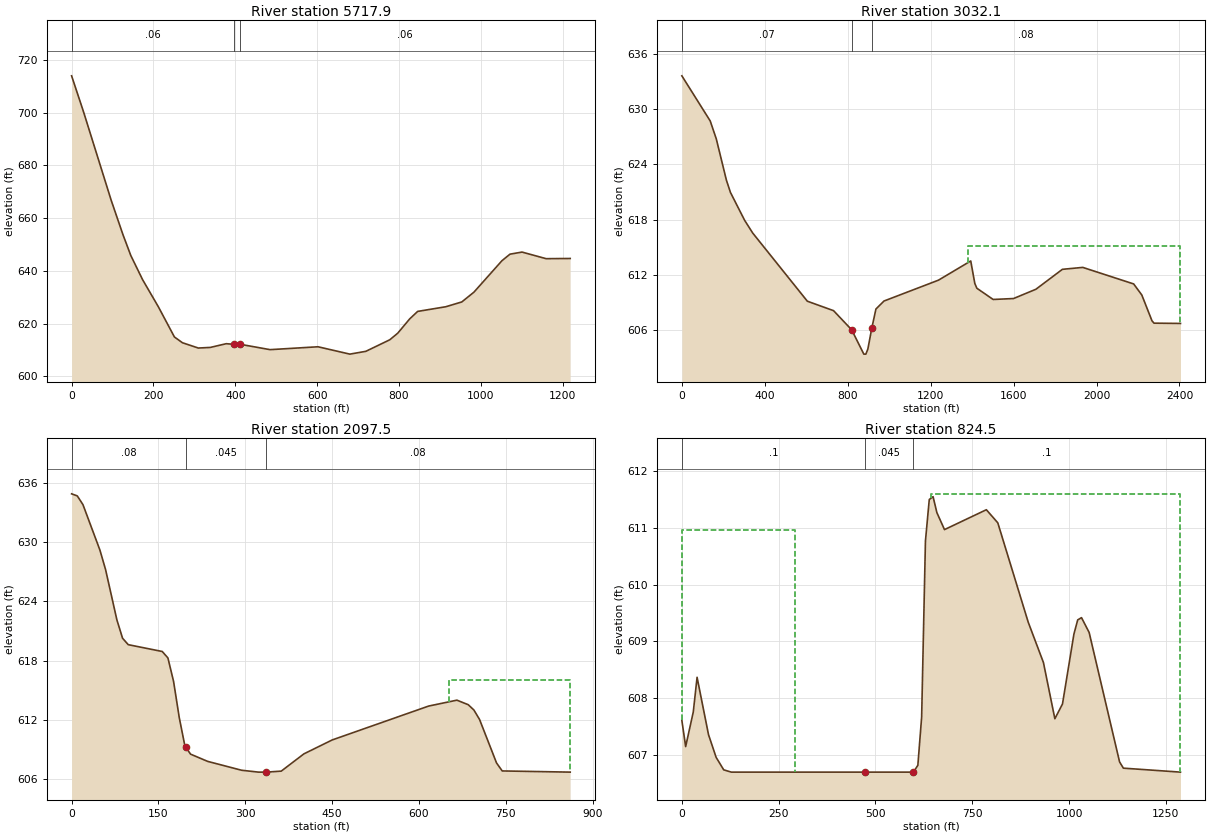
Type RM Length L Ch R = 1 ,5717.9  ,448.8,463.4,478
XS GIS Cut Line= 4
     1515448.296      354508.397     1515396.213      354714.126
       1515513.4      355336.522     1515414.442      355695.897
#Sta/Elev= 30
       0  714.02    28.9  700.49    96.5  666.91   125.4   653.8   144.7  645.83
   173.6  636.64   212.2  626.33   251.2  614.94   270.7  612.75   309.7  610.73
   338.9  610.96   377.9  612.38   396.5  612.13   411.5  612.16     485  610.12
     602  611.21   679.9  608.42   718.9  609.48   777.4  613.86   796.8  616.35
   826.1  621.79   845.6  624.63   914.2   626.4   953.4  628.22   982.9  631.91
  1051.6  643.88  1071.2  646.35  1100.6  647.14  1159.4  644.64  1218.3  644.71
#Mann= 3 , 0 , 0
       0     .06       0   396.5    .045       0   411.5     .06       0
Bank Sta=396.5,411.5
XS Rating Curve= 0 ,0
Exp/Cntr=0.3,0.1

Type RM Length L Ch R = 1 ,3032.1  ,229.5,233.9,238.4
XS GIS Cut Line= 4
     1513039.442      353119.508     1513343.261      353631.661
     1513686.143      354352.147     1513295.518      355285.306
#Sta/Elev= 30
       0  633.65   136.7  628.74     166  626.79   214.8   622.3   234.3  620.96
   302.6  617.93   341.7  616.54   605.2  609.12   731.7  608.09   819.3     606
   877.7  603.36   887.4  603.36   897.1  603.91   916.6  606.24   936.1  608.27
     975  609.14  1237.7  611.41  1393.4   613.5    1413  611.05  1422.9  610.53
  1501.4  609.31  1599.7  609.41  1707.7  610.42  1835.4  612.59  1933.6   612.8
  2179.1     611  2218.4   609.8  2267.5  606.99  2277.3  606.73    2405   606.7
#Mann= 3 , 0 , 0
       0     .07       0   819.3    .045       0   916.6     .08       0
#XS Ineff= 2 , 0
                         1379.54          615.09
Permanent Ineff=
       F       F
Bank Sta=819.3,916.6
XS Rating Curve= 0 ,0
Exp/Cntr=0.3,0.1

Type RM Length L Ch R = 1 ,2097.5  ,464.3,459.9,455
XS GIS Cut Line= 2
     1512996.039      353050.063     1512431.803      353701.105
#Sta/Elev= 30
       0  634.89     9.8  634.68    19.6   633.8      49  629.18    58.7  627.22
    78.3  622.11    88.1  620.26    97.9  619.61   156.6  618.92   166.4  618.27
   176.2  615.89     186  612.23   195.8  609.34     197  609.24   205.6  608.52
     235  607.79   293.7  606.89   323.1   606.7     336   606.7   362.2   606.8
   401.4  608.55   450.3  609.96   616.8  613.39   665.7  613.99   685.3  613.53
   695.1  612.99   704.9  612.03   734.2  607.63     744  606.82   861.5   606.7
#Mann= 3 , 0 , 0
       0     .08       0     197    .045       0     336     .08       0
#XS Ineff= 2 , 0
                          652.79          616.06
Permanent Ineff=
       F       F
Bank Sta=197,336
XS Rating Curve= 0 ,0
Exp/Cntr=0.3,0.1

Type RM Length L Ch R = 1 ,824.5   ,823.6,824.5,827.2
XS GIS Cut Line= 2
     1511576.768      352043.119     1512188.747      353175.931
#Sta/Elev= 30
       0  607.61     9.8  607.15    29.5  607.76    39.3  608.37    68.8  607.36
    88.5  606.96   108.1  606.74   127.8   606.7     473   606.7     598   606.7
   609.4  606.82   619.2  607.67     629  610.77   638.9   611.5   648.7  611.55
   658.5  611.27   678.2  610.97   786.3  611.32   815.8  611.09   894.4  609.34
   933.7  608.63   963.2  607.64   982.9   607.9  1012.4  609.13  1022.2  609.38
    1032  609.42  1051.7  609.16  1130.3  606.88  1140.1  606.77  1287.6   606.7
#Mann= 3 , 0 , 0
       0      .1       0     473    .045       0     598      .1       0
#XS Ineff= 2 , 0
           291.5  610.97  643.58           611.6
Permanent Ineff=
       F       F
Bank Sta=473,598
XS Rating Curve= 0 ,0
Exp/Cntr=0.3,0.1